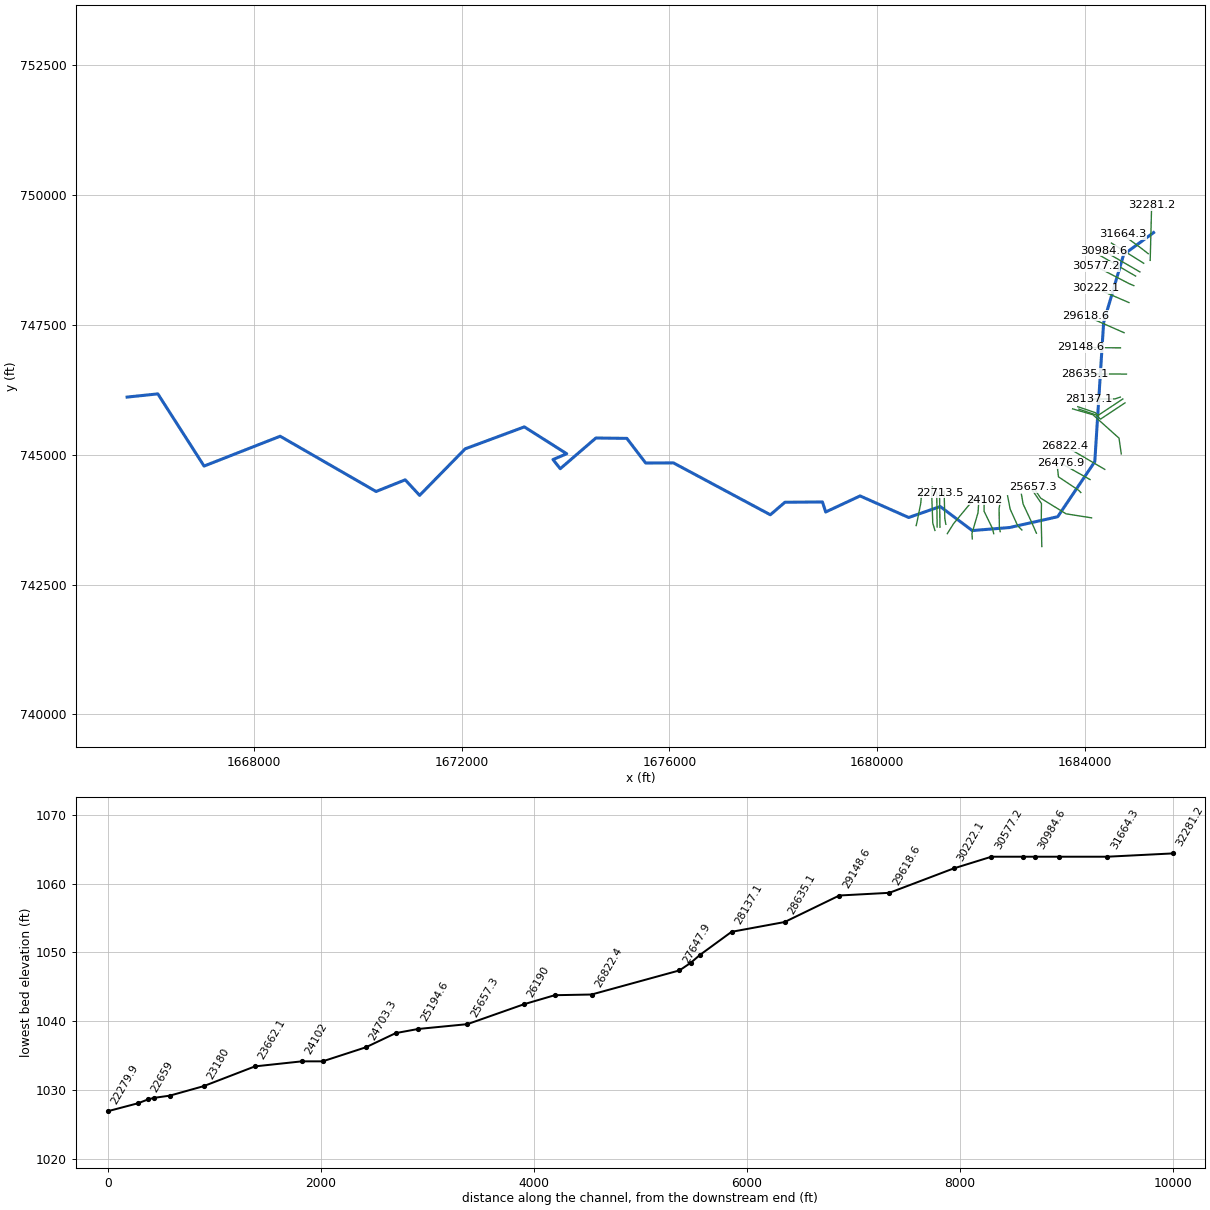
--- SFTOMLINRN.prj (project) ---

Proj Title=SFTOMLINRN
Current Plan=p01
Default Exp/Contr=0,0
English Units
Geom File=g01
Flow File=f01
Plan File=p01
BEGIN DESCRIPTION:
END DESCRIPTION:
DSS Export Rating Curves= 0
DSS Export Rating Curve Sorted= 0
DSS Export Volume Flow Curves= 0
DXF Filename=..\..\..\..\..\Engineering\Hydraulics\SFTOMLINRN\SFTOMLINRN.
DXF OffsetX= 0
DXF OffsetY= 0
DXF ScaleX= 0
DXF ScaleY= 0

--- SFTOMLINRN.p01 (plan) ---

Plan Title=Floodplain
Program Version=4.00
Geom File=g01
Flow File=f01
K Sum by GR=0
Std Step Tol=0.01
Critical Tol=0.01
Num of Std Step Trials=20
Max Error Tol=0.3
Flow Tol Ratio=0.001
Split Flow NTrial=30
Split Flow Tol=0.02
Split Flow Ratio=0.02
Log Output Level=0
Friction Slope Method=1
Unsteady Friction Slope Method=2
Unsteady Bridges Friction Slope Method=1
Global Log Level=0
CheckData=False
Run HTab=0
Run UNet=0
Run PostProcess=0
UNET Theta=0
UNET Theta Warmup=0
UNET ZTol=0
UNET ZSATol=0
UNET MxIter=0
UNET MaxInSteps=0
UNET DtIC=0
UNET DtMin=0
UNET MaxCRTS=0
UNET WFStab=0
UNET SFStab=0
UNET WFX=0
UNET SFX=0
UNET DSS MLevel=0
UNET DZMax Abort=0
UNET Convert EG Bridges=0
UNET Use Existing IB Tables=0
UNET Froude Limit=0
UNET Froude Power=0
Write IC File=0
Echo Input=False
Echo Output=False
Write Detailed=0

--- SFTOMLINRN.f01 (steady flow) ---

Flow Title=NFF Regression Equation
Program Version=4.10
Number of Profiles= 1
Profile Names=P100yr
River Rch & RM=SFTOMLINRN,Main            ,32281.2
  1170.6
River Rch & RM=SFTOMLINRN,Main            ,30984.6
    1256
River Rch & RM=SFTOMLINRN,Main            ,29148.6
    1320
River Rch & RM=SFTOMLINRN,Main            ,26822.4
1577.587
River Rch & RM=SFTOMLINRN,Main            ,23662.1
1668.347
River Rch & RM=SFTOMLINRN,Main            ,23180
1850.413
River Rch & RM=SFTOMLINRN,Main            ,20797.7
1871.885
River Rch & RM=SFTOMLINRN,Main            ,20500.7
2141.984
River Rch & RM=SFTOMLINRN,Main            ,15422
 2350.09
River Rch & RM=SFTOMLINRN,Main            ,8933.4
2580.791
River Rch & RM=SFTOMLINRN,Main            ,283.7
2848.541
Boundary for River Rch & Prof#=SFTOMLINRN,Main            , 1
Up Type= 0
Dn Type= 1
Dn Known WS=918.81
DSS Import GetInterval= 0
DSS Import GetPeak= 0
DSS Import FillOption= 0

--- SFTOMLINRN.g01 (geometry) ---

Geom Title=2003 WVU SAMB 3 Meter DEM
Program Version=4.10

River Reach=SFTOMLINRN      ,Main
Reach XY= 30
     1685326.056      749277.136     1684749.233      748853.959
     1684363.816      747546.667     1684193.243       744866.98
     1683478.846      743806.845     1682551.135      743598.672
     1681832.207      743540.561      1681215.35      744003.136
     1680607.883       743791.92     1679672.121      744207.123
     1679008.926      743898.095     1678947.294      744090.803
     1678224.204      744085.595     1677942.954      743844.276
     1676075.859      744843.253     1675541.058      744840.923
     1675178.698      745315.136     1674582.144      745322.127
     1673896.079      744731.428     1673756.056      744907.336
     1674020.544       745019.19     1673204.181      745536.425
     1672063.941      745113.468     1671186.444      744218.408
     1670909.164      744517.112     1670347.902      744292.626
     1668500.246      745356.428       1667034.1       744782.21
     1666143.909       746171.75     1665551.799      746110.023

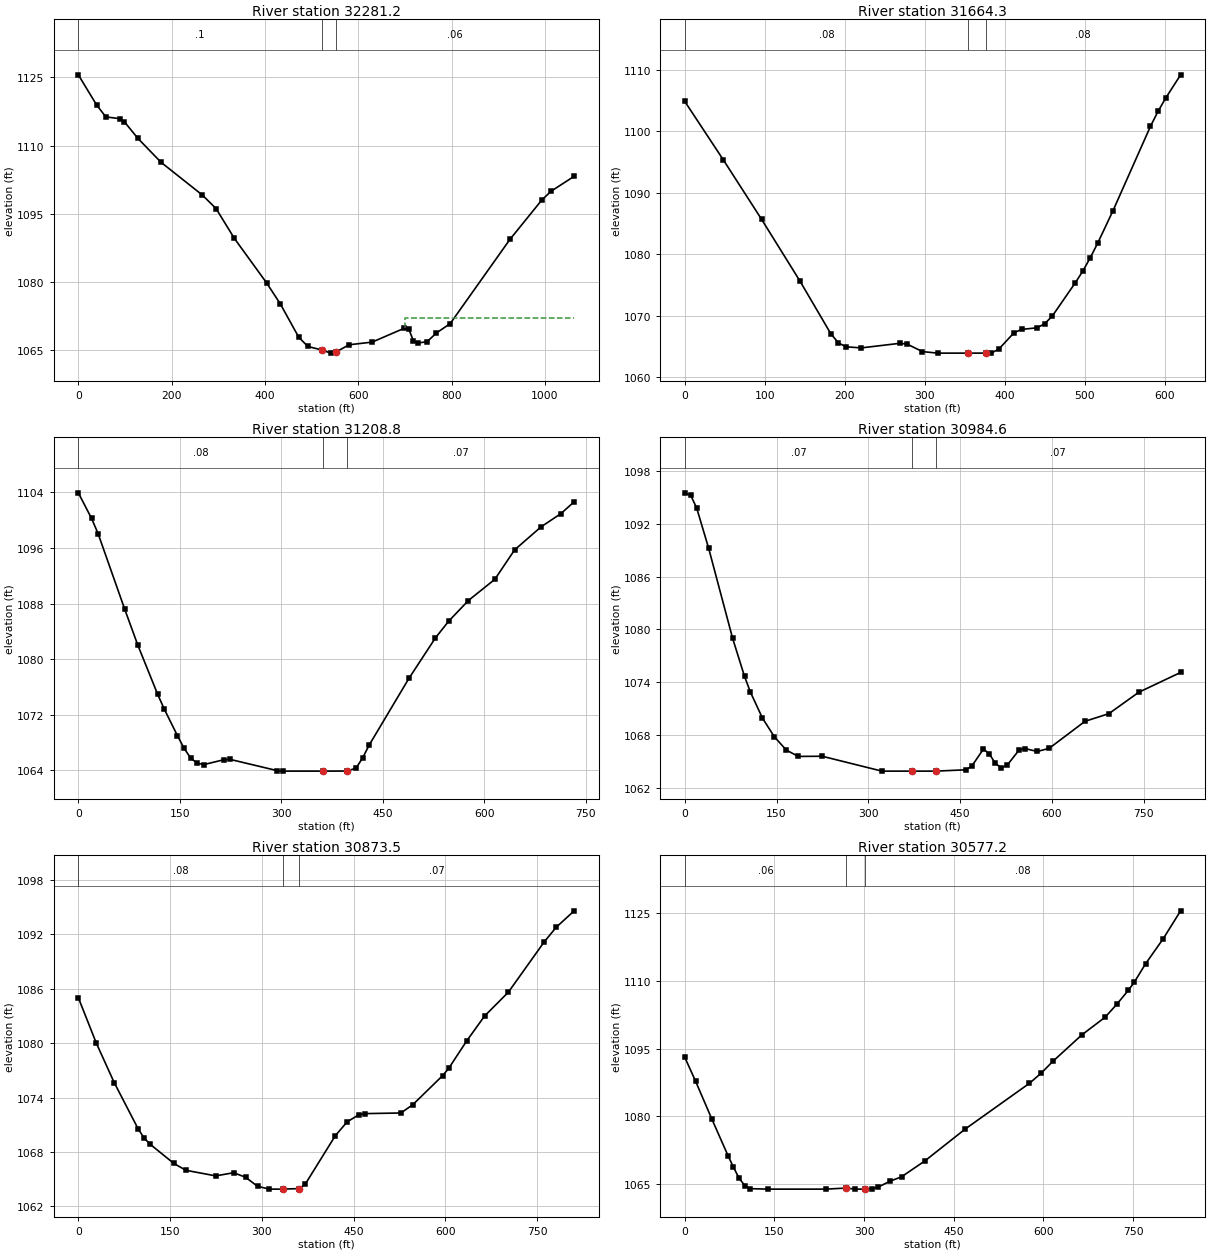
Type RM Length L Ch R = 1 ,32281.2 ,518.2,616.9,621.2
XS GIS Cut Line= 2
     1685260.789      748742.016     1685288.567      749804.516
#Sta/Elev= 30
       0 1125.55    39.4 1118.89      59  1116.3    88.6 1115.92    98.4 1115.27
   127.9 1111.56   177.1 1106.34   265.7 1099.14   295.2 1096.16   334.6 1089.58
   403.5 1079.83     433  1075.2   472.4 1067.89   492.1 1065.84   521.6 1065.09
   541.3 1064.38   552.41064.638   580.6 1066.22   629.8  1066.8   698.7 1069.85
   708.6  1069.6   718.4 1067.06   728.3  1066.6   747.9 1066.91   767.6 1068.81
   797.2 1070.87   925.1 1089.36     994 1098.09  1013.7 1099.98  1062.9 1103.25
#Mann= 3 , 0 , 0
       0      .1       0   521.6    .045       0   552.4     .06       0
#XS Ineff= 2 , 0
                          700.14         1072.14
Permanent Ineff=
       F       F
Bank Sta=521.6,552.4
XS Rating Curve= 0 ,0
Exp/Cntr=0.3,0.1

Type RM Length L Ch R = 1 ,31664.3 ,476.1,455.5,436.8
XS GIS Cut Line= 4
     1685222.594      748870.488     1685094.122      748971.183
     1684847.594      749151.738     1684729.539      749245.488
#Sta/Elev= 30
       0 1104.83      48 1095.36      96 1085.65     144  1075.6   182.3 1067.09
   191.9 1065.57   201.4 1064.93   220.5 1064.75   268.3 1065.49   277.8 1065.37
   296.9 1064.15     316  1063.9     354  1063.9     3761063.902   382.9 1063.91
   392.4 1064.55   411.5 1067.23   421.1 1067.76   440.2 1068.02   449.7 1068.68
   459.3 1069.94   487.6 1075.27   497.1 1077.18   506.5 1079.37   515.9 1081.77
   534.8 1086.98   581.9 1100.78   591.3  1103.2   600.7 1105.33   619.6 1109.16
#Mann= 3 , 0 , 0
       0     .08       0     354    .045       0     376     .08       0
Bank Sta=354,376
XS Rating Curve= 0 ,0
Exp/Cntr=0.3,0.1

Type RM Length L Ch R = 1 ,31208.8 ,232.5,224.2,216.7
XS GIS Cut Line= 2
     1685135.789       748686.46     1684514.261      749075.349
#Sta/Elev= 30
       0 1103.93    19.6 1100.24    29.3 1098.04    68.4 1087.24      88 1082.01
   117.3 1074.95   127.1 1072.82   146.6 1068.99   156.4 1067.18   166.2 1065.77
     176 1065.03   185.7 1064.84   215.1 1065.54   224.8 1065.58   293.3 1063.99
     303  1063.9   361.7  1063.9     3971063.911   410.6 1064.32   420.4  1065.8
   430.1 1067.65   488.8 1077.23   527.9 1083.04   547.4 1085.44   576.8 1088.44
   615.9 1091.49   645.2 1095.73   684.3 1099.04   713.6 1100.94   733.2 1102.64
#Mann= 3 , 0 , 0
       0     .08       0   361.7    .045       0     397     .07       0
Bank Sta=361.7,397
XS Rating Curve= 0 ,0
Exp/Cntr=0.3,0.1

Type RM Length L Ch R = 1 ,30984.6 ,111.1,111.1,111.1
XS GIS Cut Line= 2
     1685062.872      748519.794     1684361.483      748926.044
#Sta/Elev= 30
       0 1095.51     9.8 1095.21    19.5 1093.77    39.1 1089.19    78.1    1079
    97.7 1074.65   107.4 1072.85     127 1069.92   146.5 1067.79     166 1066.29
   185.6 1065.57   224.6 1065.59   322.3  1063.9     372  1063.9   410.2  1063.9
     459 1064.05   468.8 1064.43   488.3 1066.42     498 1065.84   507.8 1064.77
   517.6 1064.27   527.3  1064.6   546.9 1066.33   556.6 1066.46   576.2 1066.13
   595.7 1066.49   654.3 1069.56   693.4 1070.43   742.2 1072.86   810.6 1075.11
#Mann= 3 , 0 , 0
       0     .07       0     372    .045       0   410.2     .07       0
Bank Sta=372,410.2
XS Rating Curve= 0 ,0
Exp/Cntr=0.3,0.1

Type RM Length L Ch R = 1 ,30873.5 ,297.3,296.3,288.7
XS GIS Cut Line= 2
     1684979.539      748439.933      1684278.15      748846.183
#Sta/Elev= 30
       0 1085.02    29.3 1080.02    58.6 1075.66    97.7 1070.56   107.4 1069.55
   117.2 1068.86   156.2 1066.73   175.8 1065.98   224.6 1065.36   253.9 1065.71
   273.4 1065.21     293 1064.21   312.5  1063.9   333.8  1063.9   361.3 1063.96
   371.1 1064.46   419.9 1069.77   439.4 1071.32     459 1072.12   468.8 1072.23
   527.3  1072.3   546.9 1073.22   595.7 1076.43   605.5 1077.22   634.8 1080.24
   664.1 1082.99   703.1 1085.63   761.7 1091.18   781.2 1092.78   810.6  1094.6
#Mann= 3 , 0 , 0
       0     .08       0   333.8    .045       0   361.3     .07       0
Bank Sta=333.8,361.3
XS Rating Curve= 0 ,0
Exp/Cntr=0.3,0.1

Type RM Length L Ch R = 1 ,30577.2 ,352.7,355.1,355.8
XS GIS Cut Line= 3
     1684944.817      748255.905     1684861.483      748290.627
     1684205.233      748630.905
#Sta/Elev= 30
       0  1093.1    18.1 1087.79    45.1 1079.47    72.2 1071.35    81.2  1068.8
    90.3 1066.46     100  1064.7   109.7    1064   138.9  1063.9   236.2  1063.9
     2701064.139   284.8  1063.9   302.2  1063.9     314    1064   323.7 1064.37
   343.2 1065.65   362.6 1066.63   401.5 1070.14   469.6 1077.26   576.6 1087.35
   596.1 1089.58   615.5 1092.18   664.2 1098.07   703.1 1101.98   722.5 1104.82
     742 1107.94   751.7 1109.69   771.1 1113.88   800.3 1119.36   829.5 1125.56
#Mann= 3 , 0 , 0
       0     .06       0     270    .045       0   302.2     .08       0
Bank Sta=270,302.2
XS Rating Curve= 0 ,0
Exp/Cntr=0.3,0.1

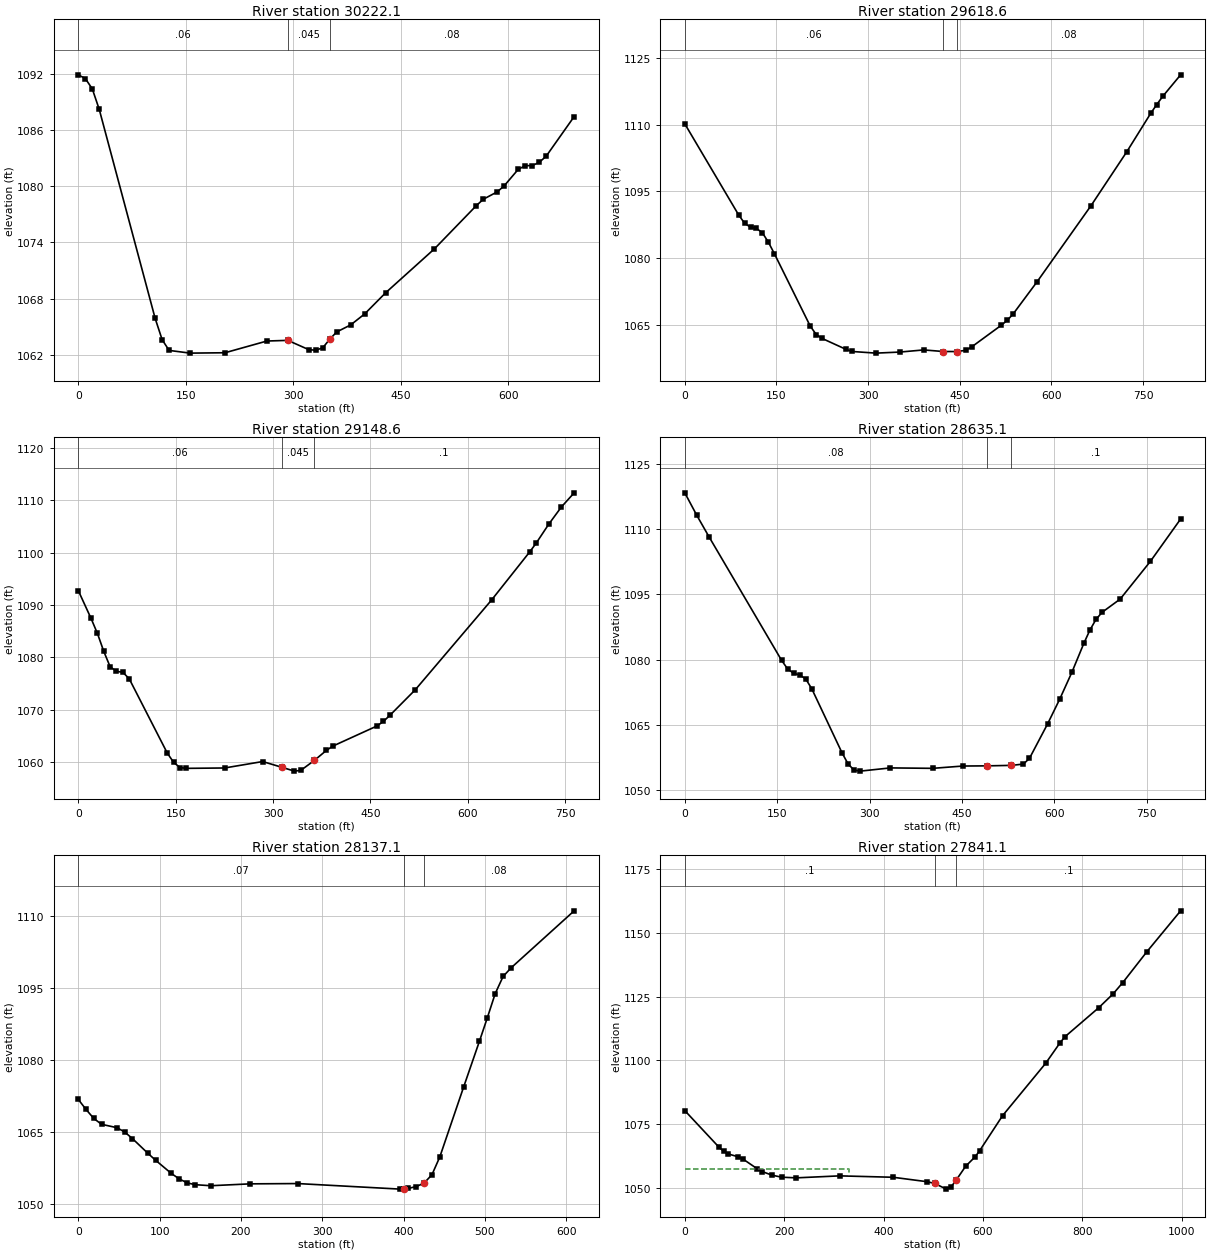
Type RM Length L Ch R = 1 ,30222.1 ,603.2,603.5,603.6
XS GIS Cut Line= 2
     1684851.067      747929.516      1684215.65      748203.821
#Sta/Elev= 30
       0 1091.87     9.8 1091.47    19.5 1090.37    29.2 1088.18   107.2 1065.91
     117 1063.63   126.7 1062.49     156  1062.2   204.7 1062.24   263.2 1063.49
   292.4 1063.56   321.7 1062.57   331.4 1062.51   341.2 1062.77   350.9 1063.68
   360.7 1064.46   380.2 1065.21   399.7 1066.38   428.9 1068.63   497.1 1073.32
   555.6 1077.93   565.4 1078.61   584.9  1079.4   594.6 1080.05   614.1  1081.8
   623.9 1082.18   633.6  1082.2   643.4 1082.54   653.1  1083.2   692.1 1087.42
#Mann= 3 , 0 , 0
       0     .06       0   292.4    .045       0   350.9     .08       0
Bank Sta=292.4,350.9
XS Rating Curve= 0 ,0
Exp/Cntr=0.3,0.1

Type RM Length L Ch R = 1 ,29618.6 ,459.2,470,478.4
XS GIS Cut Line= 2
     1684757.317      747349.655     1684014.261      747676.044
#Sta/Elev= 30
       0 1110.17      88 1089.74    97.8 1087.85   107.6 1086.94   117.3 1086.68
   127.1 1085.68   136.9 1083.56   146.7 1080.98   205.3 1064.74   215.1 1062.84
   224.9 1061.95     264  1059.5   273.8 1059.03   312.9 1058.66     352  1058.9
   391.1 1059.38     4231059.025     4451059.015   459.6 1059.28   469.4 1060.04
   518.2 1064.94     528 1066.05   537.8 1067.52   576.9 1074.74   664.9 1091.78
   723.6 1103.92   762.7 1112.54   772.5  1114.5   782.2 1116.32   811.6 1121.18
#Mann= 3 , 0 , 0
       0     .06       0     423    .045       0     445     .08       0
Bank Sta=423,445
XS Rating Curve= 0 ,0
Exp/Cntr=0.3,0.1

Type RM Length L Ch R = 1 ,29148.6 ,513.4,513.5,513.4
XS GIS Cut Line= 2
     1684687.872      747057.988     1683923.983      747064.933
#Sta/Elev= 30
       0 1092.72    19.6 1087.42    29.4 1084.56    39.2 1081.13      49 1078.19
    58.8 1077.32    68.6 1077.14    78.4  1075.9   137.1  1061.7   146.9 1059.93
   156.7 1058.95   166.5  1058.8   225.3 1058.87     284  1060.1   313.4 1059.01
     333 1058.27   342.8 1058.42   363.6 1060.31     382 1062.21   391.8 1063.03
   460.3  1066.9   470.1 1067.77   479.9 1068.91   519.1  1073.8   636.6 1090.93
   695.4 1100.12   705.2 1101.76   724.8 1105.42   744.3 1108.71   763.9  1111.4
#Mann= 3 , 0 , 0
       0     .06       0   313.4    .045       0   363.6      .1       0
Bank Sta=313.4,363.6
XS Rating Curve= 0 ,0
Exp/Cntr=0.3,0.1

Type RM Length L Ch R = 1 ,28635.1 ,497.3,498,498.1
XS GIS Cut Line= 2
     1684803.324       746552.78     1683998.636      746557.988
#Sta/Elev= 30
       0  1118.3    19.6  1113.1    39.2 1108.23     157 1079.87   166.8 1077.89
   176.6 1076.87   186.5  1076.5   196.3 1075.57   206.1 1073.32   255.2 1058.61
     265 1056.07   274.8 1054.64   284.6 1054.42   333.7 1055.16   402.4 1055.06
   451.4 1055.59   490.7 1055.63   529.9 1055.74   549.6 1056.04   559.4 1057.36
   588.8 1065.26   608.4 1070.92   628.1 1077.07   647.7 1083.77   657.5 1086.81
   667.3 1089.23   677.1 1090.86   706.6 1093.91   755.6 1102.56   804.7 1112.29
#Mann= 3 , 0 , 0
       0     .08       0   490.7    .045       0   529.9      .1       0
Bank Sta=490.7,529.9
XS Rating Curve= 0 ,0
Exp/Cntr=0.3,0.1

Type RM Length L Ch R = 1 ,28137.1 ,282.9,296,308.8
XS GIS Cut Line= 3
     1684685.865      746110.122     1684586.906      746076.268
     1684081.698       746071.06
#Sta/Elev= 30
       0 1071.69     9.5 1069.61      19 1067.74    28.5 1066.52    47.5 1065.81
      57 1064.91    66.6 1063.53    85.6 1060.46    95.1 1059.01   114.3 1056.28
     124 1055.14   133.7 1054.32   143.4 1053.93   162.9 1053.71   211.5  1054.1
   269.8 1054.16   396.1    1053     4001053.056   405.8 1053.14   415.5 1053.54
     4251054.225   434.9    1056   444.6 1059.73   473.8 1074.26   493.2 1083.79
     503 1088.72   512.7 1093.77   522.4 1097.34   532.1 1099.12   609.8 1111.03
#Mann= 3 , 0 , 0
       0     .07       0     400    .045       0     425     .08       0
Bank Sta=400,425
XS Rating Curve= 0 ,0
Exp/Cntr=0.3,0.1

Type RM Length L Ch R = 1 ,27841.1 ,87.8,87.7,87.6
XS GIS Cut Line= 4
     1684733.011      746073.613     1684261.657      745761.113
     1684196.553      745813.196     1683865.824      745925.176
#Sta/Elev= 30
       0 1080.38    68.2 1066.19      78 1064.47    87.8  1063.4   107.3 1062.32
     117 1061.44   146.3 1057.55     156 1056.52   175.5 1055.12     195 1054.33
   224.3 1054.07     312 1054.85   419.3  1054.3   487.5 1052.57   502.71051.913
   526.5 1049.66   536.3  1050.6     546 1053.11   565.5 1058.65   584.1 1062.23
   593.3 1064.62   639.6 1078.38   726.5  1098.9   755.6 1106.97   765.3 1109.28
   833.2 1120.62   862.3 1126.07   881.7 1130.47   930.2 1142.54   998.1 1158.53
#Mann= 3 , 0 , 0
       0      .1       0   502.7    .045       0     546      .1       0
#XS Ineff= 2 , 0
          331.03 1057.39
Permanent Ineff=
       F       F
Bank Sta=502.7,546
XS Rating Curve= 0 ,0
Exp/Cntr=0.3,0.1

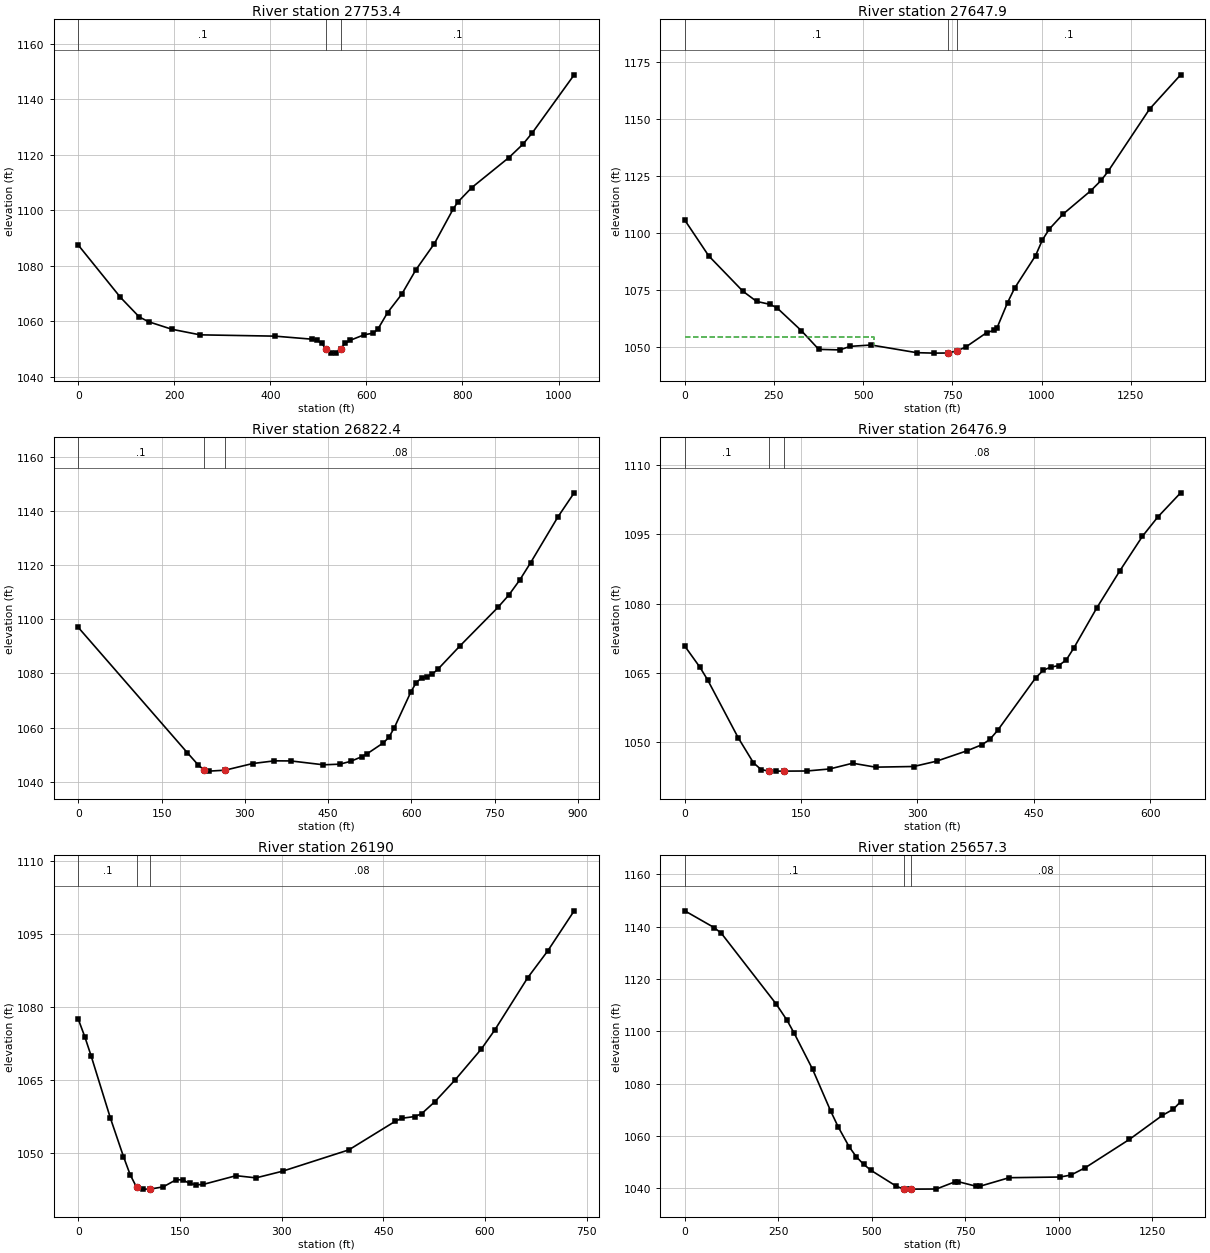
Type RM Length L Ch R = 1 ,27753.4 ,135.8,105.5,74.7
XS GIS Cut Line= 4
     1684774.678      745998.092     1684303.324      745685.592
     1684217.386      745766.321     1683886.657      745878.301
#Sta/Elev= 30
       0 1087.41    87.8 1068.58   126.8 1061.55   146.3 1059.81     195 1057.09
   253.5 1055.09   409.5 1054.62   487.5 1053.51   497.3 1053.13     507 1051.97
   516.8 1049.81   526.5  1048.5   536.3 1048.61     546 1050.16   555.8 1052.03
   565.5 1053.07     595  1055.1   614.7 1055.72   624.5 1057.34   644.1 1063.12
   673.6 1069.75   702.8 1078.48   741.6    1088   780.4 1100.36   790.1 1102.89
   819.2 1108.13   896.8 1118.99   925.9 1123.78   945.3 1127.86  1032.6 1148.79
#Mann= 3 , 0 , 0
       0      .1       0   516.8    .045       0     546      .1       0
Bank Sta=516.8,546
XS Rating Curve= 0 ,0
Exp/Cntr=0.3,0.1

Type RM Length L Ch R = 1 ,27647.9 ,820.6,825.5,828.5
XS GIS Cut Line= 4
     1684703.497      745015.453     1684660.094      745319.273
     1684156.622      745770.662     1683765.997      745883.509
#Sta/Elev= 30
       0  1105.7    67.1 1090.02     163 1074.51   201.4 1070.06   239.8 1068.75
     259 1067.16   326.5 1057.27   375.5 1049.05   434.3 1048.81   463.7 1050.37
   522.5 1050.96   649.9  1047.6   698.9  1047.4     7381047.459     7621048.366
   787.1 1050.03   845.9 1056.36   865.5 1057.35   875.3 1058.54   904.7 1069.56
   924.3 1075.86   983.1 1090.13  1002.5 1097.08  1021.8 1101.82  1060.5 1108.38
    1138  1118.6    1167 1123.13  1186.4 1127.08  1302.6 1154.37  1389.7 1169.39
#Mann= 3 , 0 , 0
       0      .1       0     738    .045       0     762      .1       0
#XS Ineff= 2 , 0
          531.03 1054.57
Permanent Ineff=
       F       F
Bank Sta=738,762
XS Rating Curve= 0 ,0
Exp/Cntr=0.3,0.1

Type RM Length L Ch R = 1 ,26822.4 ,345.2,345.5,345.5
XS GIS Cut Line= 2
     1684385.713      744718.332      1683614.88      745169.721
#Sta/Elev= 30
       0    1097   196.3 1050.72     216 1046.18   225.8 1044.44   235.6  1043.9
   264.31044.243   314.1 1046.71   353.4  1047.7   382.8 1047.67   441.7 1046.24
   471.2 1046.47   490.8 1047.53   510.4  1049.2   520.3 1050.32   549.7 1054.37
   559.5 1056.41   569.3 1059.95   598.8 1073.04   608.6 1076.59   618.4 1078.38
   628.2 1078.84     638 1079.83   647.9 1081.58   687.1 1090.09   755.8 1104.39
   775.5 1108.96   795.1 1114.49   814.7 1120.89   863.8 1137.79   893.3 1146.77
#Mann= 3 , 0 , 0
       0      .1       0   225.8    .045       0   264.3     .08       0
Bank Sta=225.8,264.3
XS Rating Curve= 0 ,0
Exp/Cntr=0.3,0.1

Type RM Length L Ch R = 1 ,26476.9 ,288.8,286.9,284.4
XS GIS Cut Line= 2
     1684101.494      744522.488     1683543.768      744834.988
#Sta/Elev= 30
       0 1070.82    19.7 1066.21    29.5  1063.5    68.8 1051.03    88.5  1045.6
    98.4 1044.14   108.2 1043.81     118  1043.8   127.9  1043.8   157.4 1043.83
   186.9 1044.27   216.4 1045.51   245.9 1044.66   295.1  1044.8   324.6 1045.95
   363.9  1048.2   383.6 1049.54   393.4 1050.67   403.3 1052.59   452.4 1063.96
   462.3 1065.62   472.1 1066.29   481.9  1066.6   491.8 1067.82   501.6 1070.41
   531.1 1079.05   560.6 1087.01   590.1 1094.57   609.8 1098.71   639.3 1103.95
#Mann= 3 , 0 , 0
       0      .1       0   108.2    .045       0   127.9     .08       0
Bank Sta=108.2,127.9
XS Rating Curve= 0 ,0
Exp/Cntr=0.3,0.1

Type RM Length L Ch R = 1 ,26190   ,532.6,532.8,531.1
XS GIS Cut Line= 4
     1683923.542      744272.922      1683884.48      744314.155
     1683493.855      744574.571     1683469.983      744778.564
#Sta/Elev= 30
       0 1077.48     9.5 1073.91    18.9 1069.94    47.3 1057.14    66.6 1049.21
    76.4  1045.5    86.1 1042.84    95.9  1042.5   105.7  1042.5   125.3 1042.97
   144.8 1044.47   154.6 1044.37   164.4 1043.66   174.2  1043.4     184 1043.46
   232.8 1045.27   262.2 1044.82   301.3 1046.19   399.1 1050.58   467.6 1056.47
   477.4  1057.1   496.9 1057.46   506.7 1058.05   526.3 1060.53   555.6 1064.93
   594.7 1071.36   614.3 1075.23   663.2 1086.06   692.5 1091.53   731.7 1099.83
#Mann= 3 , 0 , 0
       0      .1       0    86.1    .045       0   105.7     .08       0
Bank Sta=86.1,105.7
XS Rating Curve= 0 ,0
Exp/Cntr=0.3,0.1

Type RM Length L Ch R = 1 ,25657.3 ,485.7,462.6,437.9
XS GIS Cut Line= 4
     1684131.109      743785.147     1683639.254      743862.766
     1683150.973      744164.415     1683007.744      744374.919
#Sta/Elev= 30
       0 1146.08    78.1  1139.7    97.6 1137.52   244.1  1110.5   273.4 1104.23
   292.9 1099.18   341.7 1085.52   390.5 1069.41   410.1 1063.49   439.4 1055.87
   458.9 1051.96   478.4  1049.1   497.9 1046.81     566  1040.7   585.5 1039.63
   595.2  1039.6   605.2  1039.6     673 1039.64   721.7 1042.34   731.4 1042.45
     780 1040.68   789.8 1040.71   867.6 1043.97  1003.8 1044.23    1033 1044.98
  1071.9 1047.84  1189.4 1058.62  1277.5  1067.8  1306.9 1070.17  1326.5 1073.06
#Mann= 3 , 0 , 0
       0      .1       0   585.5    .045       0   605.2     .08       0
Bank Sta=585.5,605.2
XS Rating Curve= 0 ,0
Exp/Cntr=0.3,0.1

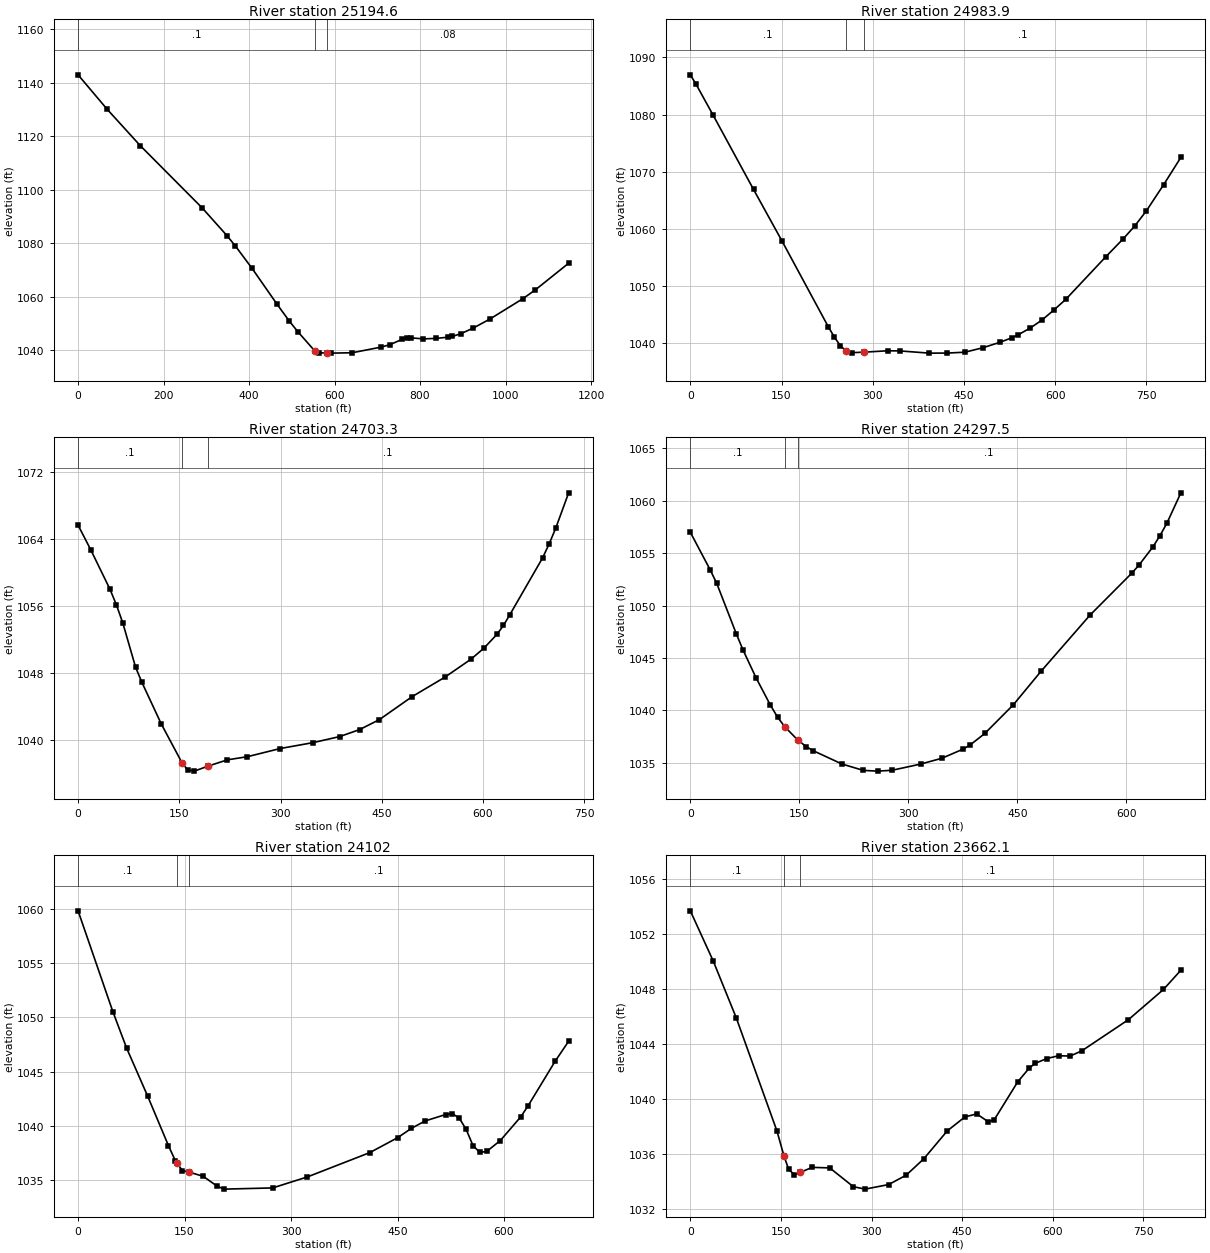
Type RM Length L Ch R = 1 ,25194.6 ,200.4,210.7,221.1
XS GIS Cut Line= 4
     1683172.776      743233.064     1683161.824      743717.367
     1683166.164      744060.249     1682986.042      744325.005
#Sta/Elev= 30
       0 1143.02    67.8 1130.18   145.3 1116.55   290.7 1093.17   348.8 1082.77
   368.2 1078.94   406.9 1070.64     465  1057.3   494.2 1050.87   513.8 1046.98
   553.5 1039.76   562.8 1039.03   582.4 1038.93   592.2  1038.9   641.2 1039.04
   709.8 1041.18   729.4 1042.06   758.8 1044.11   768.6 1044.51   778.4 1044.62
   807.7 1044.23     837 1044.41   866.2 1044.87   875.8 1045.16   895.3 1046.16
   924.4 1048.27   963.2 1051.63  1040.8  1059.3  1069.9 1062.59  1147.6 1072.54
#Mann= 3 , 0 , 0
       0      .1       0   553.5    .045       0   582.4     .08       0
Bank Sta=553.5,582.4
XS Rating Curve= 0 ,0
Exp/Cntr=0.3,0.1

Type RM Length L Ch R = 1 ,24983.9 ,279.9,280.6,280.6
XS GIS Cut Line= 4
     1683068.609      743490.008     1682981.702      743689.155
     1682812.431      744051.568     1682779.879        744238.2
#Sta/Elev= 30
       0 1086.96     9.4 1085.32    37.8 1079.85   103.9 1066.93   151.2 1057.82
     227 1042.89   236.8 1041.12   246.6 1039.61     256 1038.71   266.1 1038.38
   285.6 1038.47   324.6 1038.71   344.1 1038.69   392.9  1038.3   422.2 1038.31
   451.4 1038.46   480.7 1039.23     510 1040.22   529.5 1041.02   539.2 1041.51
   558.7 1042.67   578.2 1044.08   597.8 1045.83   617.3 1047.69   683.6 1055.19
     712  1058.3     731 1060.55   749.9 1063.17   778.3 1067.74   806.7 1072.53
#Mann= 3 , 0 , 0
       0      .1       0     256    .045       0   285.6      .1       0
Bank Sta=256,285.6
XS Rating Curve= 0 ,0
Exp/Cntr=0.3,0.1

Type RM Length L Ch R = 1 ,24703.3 ,416.4,405.8,391.5
XS GIS Cut Line= 4
      1682788.56      743552.436     1682708.265      743632.731
     1682562.865      743953.912     1682512.952      744209.988
#Sta/Elev= 30
       0 1065.62    18.9 1062.66    47.3 1057.96    56.8  1056.1    66.2 1053.96
    85.2 1048.66    94.6 1046.84   123.4 1041.86   154.2 1037.21   162.5 1036.38
   172.3 1036.24   191.9 1036.82   221.3 1037.59   250.7 1037.96   299.6 1038.94
   348.6 1039.65   387.8 1040.37   417.2  1041.2   446.5 1042.39   495.1 1045.14
   543.4 1047.45   582.1  1049.6   601.4 1050.92   620.7 1052.57   630.4 1053.64
     640 1054.94   688.4 1061.71     698 1063.36   707.7 1065.22     727 1069.48
#Mann= 3 , 0 , 0
       0      .1       0   154.2    .045       0   191.9      .1       0
Bank Sta=154.2,191.9
XS Rating Curve= 0 ,0
Exp/Cntr=0.3,0.1

Type RM Length L Ch R = 1 ,24297.5 ,185.2,195.5,203.5
XS GIS Cut Line= 4
     1682371.893      743519.884     1682354.532       743608.86
     1682350.192      743962.592     1682384.914      744190.457
#Sta/Elev= 30
       0 1056.99    27.2 1053.42    36.3 1052.12    63.5 1047.26    72.5 1045.76
    90.6 1043.08   110.3 1040.48   120.1 1039.34     130 1038.43   147.5 1037.19
   159.4 1036.54   169.3 1036.14   208.6 1034.88     238 1034.27   257.7  1034.2
   277.4 1034.28   316.7 1034.87   346.2 1035.43   375.6 1036.31   385.4 1036.72
   405.1 1037.79   444.4 1040.53   482.8 1043.75   550.1  1049.1   607.7 1053.11
   617.3 1053.86   636.5  1055.6   646.1 1056.66   655.7 1057.86   674.9 1060.75
#Mann= 3 , 0 , 0
       0      .1       0     130    .045       0   147.5      .1       0
Bank Sta=130,147.5
XS Rating Curve= 0 ,0
Exp/Cntr=0.3,0.1

Type RM Length L Ch R = 1 ,24102   ,450.9,439.9,421.6
XS GIS Cut Line= 4
     1682246.025      743480.821     1682224.324      743576.308
     1682061.563      743910.509     1682059.393      744131.863
#Sta/Elev= 30
       0 1059.79      49 1050.52    68.5 1047.15    97.9 1042.77   127.3  1038.2
     137 1036.81   138.8 1036.64   146.8 1035.91   156.6 1035.76   176.2 1035.38
   195.7 1034.48   205.5  1034.2     274 1034.31   322.9 1035.32     411 1037.56
   450.1 1038.93   469.6 1039.79   488.9 1040.47   517.8 1041.06   527.4 1041.14
     537 1040.72   546.6  1039.7   556.3  1038.2   565.9 1037.58   575.5 1037.66
   594.8 1038.67   623.6 1040.85   633.3  1041.8   671.8 1045.94     691  1047.8
#Mann= 3 , 0 , 0
       0      .1       0   138.8    .045       0   156.6      .1       0
Bank Sta=138.8,156.6
XS Rating Curve= 0 ,0
Exp/Cntr=0.3,0.1

Type RM Length L Ch R = 1 ,23662.1 ,486.1,482.1,440.9
XS GIS Cut Line= 4
     1681833.699      743380.995     1681827.188      743485.162
     1681944.376      743886.637     1681963.907      744175.266
#Sta/Elev= 30
       0 1053.67      38 1050.02    75.9 1045.92   143.3  1037.7   154.8 1035.91
   162.7 1034.91   172.4 1034.51   182.2 1034.69   201.6 1035.05   230.8 1035.01
   269.7 1033.65   289.2 1033.47   328.1  1033.8   357.2 1034.48   386.4 1035.67
   425.3  1037.7   454.5 1038.71     474 1038.93   493.4 1038.35   503.2 1038.52
   541.9 1041.26   561.2 1042.27   570.8  1042.6   590.1 1042.95   609.4 1043.15
   628.7 1043.13     648 1043.51   725.1 1045.77     783 1047.96   811.9 1049.36
#Mann= 3 , 0 , 0
       0      .1       0   154.8    .045       0   182.2      .1       0
Bank Sta=154.8,182.2
XS Rating Curve= 0 ,0
Exp/Cntr=0.3,0.1

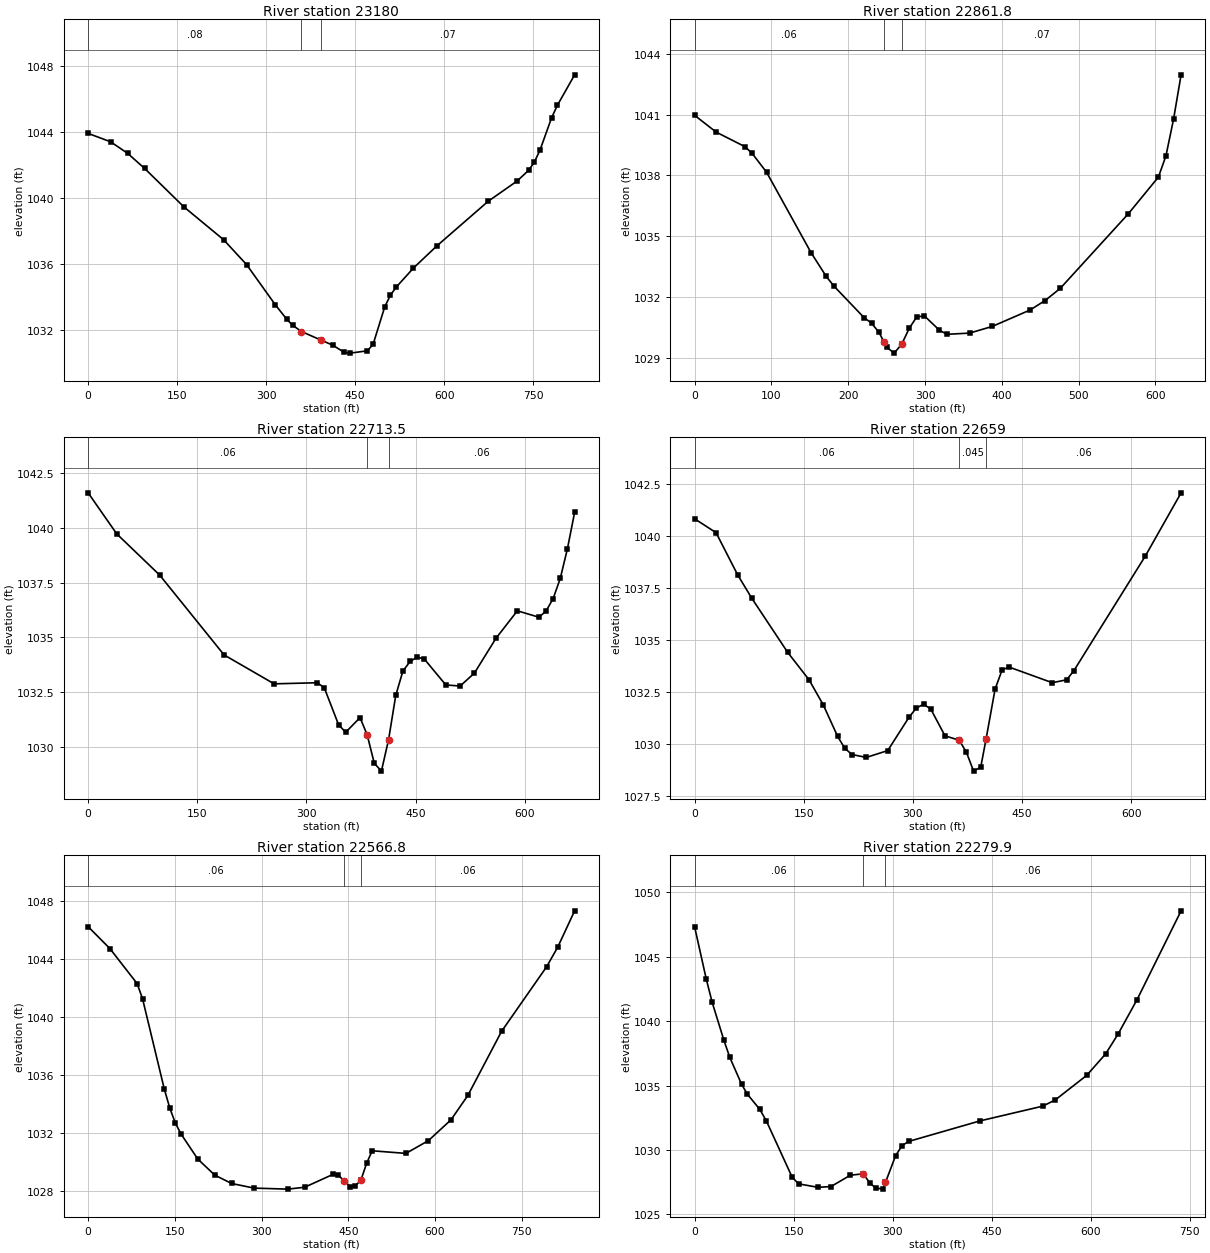
Type RM Length L Ch R = 1 ,23180   ,299.5,318.2,338
XS GIS Cut Line= 3
     1681351.928      743480.821     1681473.456      743673.964
      1681851.06      744129.693
#Sta/Elev= 30
       0 1043.92      38 1043.41    66.6 1042.71    95.1  1041.8   161.6 1039.46
   228.2 1037.48     267 1035.97   315.5 1033.53   334.9 1032.65   344.6 1032.29
   359.6 1031.91   393.1 1031.38   412.5 1031.08   431.9 1030.64   441.6  1030.6
   470.8 1030.74   480.4 1031.14   499.9  1033.4   509.6 1034.12   519.3  1034.6
   548.4 1035.76   587.2 1037.08   674.5 1039.81     723 1041.03   742.4 1041.68
   752.1 1042.18   761.8 1042.92   781.2 1044.87   790.9 1045.62     820 1047.47
#Mann= 3 , 0 , 0
       0     .08       0   359.6    .045       0   393.1     .07       0
Bank Sta=359.6,393.1
XS Rating Curve= 0 ,0
Exp/Cntr=0.3,0.1

Type RM Length L Ch R = 1 ,22861.8 ,147.4,148.4,146.7
XS GIS Cut Line= 3
     1681323.716      743660.943     1681304.185       743771.62
     1681291.164      744292.453
#Sta/Elev= 30
       0 1040.97    28.1 1040.14    65.6 1039.42    74.9 1039.09    93.7 1038.16
   151.7 1034.18   171.4 1033.01   181.2 1032.54   220.5 1030.98   230.4  1030.7
   240.2 1030.24   246.6 1029.77     250 1029.52   259.8 1029.22   269.7 1029.66
   279.5 1030.45   289.3 1031.01   299.2 1031.06   318.8 1030.35   328.6 1030.15
   358.1 1030.21   387.6 1030.54   436.8 1031.35   456.4 1031.82   476.1 1032.42
   564.6  1036.1   603.9 1037.92   613.7 1038.97   623.6 1040.78   633.4 1042.97
#Mann= 3 , 0 , 0
       0     .06       0   246.6    .045       0   269.7     .07       0
Bank Sta=246.6,269.7
XS Rating Curve= 0 ,0
Exp/Cntr=0.3,0.1

Type RM Length L Ch R = 1 ,22713.5 ,54.3,54.5,54.3
XS GIS Cut Line= 2
     1681210.869      743604.519     1681202.188      744272.922
#Sta/Elev= 30
       0 1041.59    39.3 1039.72    98.3 1037.84   186.8  1034.2   255.6 1032.88
   314.6 1032.93   324.4 1032.71   344.1 1031.02   353.9 1030.67   373.6 1031.34
   383.4 1030.56   393.2 1029.26     403  1028.9   412.9 1030.34   422.7 1032.35
   432.5 1033.46   442.4  1033.9   452.2  1034.1     462 1034.01   491.5 1032.83
   511.2 1032.78   530.8 1033.37   560.3 1034.95   589.8 1036.21   619.3 1035.92
   629.1 1036.19     639 1036.77   648.8 1037.69   658.6 1039.04   668.5  1040.7
#Mann= 3 , 0 , 0
       0     .06       0   383.4    .045       0   412.9     .06       0
Bank Sta=383.4,412.9
XS Rating Curve= 0 ,0
Exp/Cntr=0.3,0.1

Type RM Length L Ch R = 1 ,22659   ,91.6,92.1,92.4
XS GIS Cut Line= 2
     1681156.615       743608.86     1681147.935      744277.262
#Sta/Elev= 30
       0 1040.84    29.5 1040.17      59 1038.15    78.6 1037.01   127.8 1034.41
   157.3 1033.08     177 1031.86   196.6 1030.35   206.4 1029.78   216.3 1029.48
   235.9 1029.34   265.4 1029.67   294.9 1031.29   304.7 1031.72   314.6  1031.9
   324.4 1031.68   344.1 1030.38   363.7 1030.17   373.6 1029.58   383.4 1028.68
   393.2 1028.87   400.6 1030.24   412.9 1032.63   422.7 1033.57   432.5 1033.69
   491.5 1032.94   511.2 1033.08     521 1033.51   619.3 1039.04   668.5 1042.09
#Mann= 3 , 0 , 0
       0     .06       0   363.7    .045       0   400.6     .06       0
Bank Sta=363.7,400.6
XS Rating Curve= 0 ,0
Exp/Cntr=0.3,0.1

Type RM Length L Ch R = 1 ,22566.8 ,290.8,287,278.9
XS GIS Cut Line= 4
     1681113.748      743542.092      1681071.98      743686.985
     1681052.449      744212.158     1681063.299      744377.089
#Sta/Elev= 30
       0  1046.2    37.7 1044.69    84.8 1042.28    94.2 1041.23   131.9    1035
   141.4  1033.7   150.8 1032.69   160.5 1031.94   189.7  1030.2   218.9  1029.1
   248.1 1028.52     287  1028.2   345.4 1028.13   374.6 1028.26   423.3 1029.14
     433 1029.09   442.8 1028.69   453.4  1028.3   462.2 1028.35     472 1028.76
   481.7  1029.9   491.4 1030.77   549.8 1030.59   588.7 1031.47   627.7  1032.9
   656.9 1034.58   715.2 1038.99     793 1043.43   812.4 1044.79   841.6 1047.29
#Mann= 3 , 0 , 0
       0     .06       0   442.8    .045       0     472     .06       0
Bank Sta=442.8,472
XS Rating Curve= 0 ,0
Exp/Cntr=0.3,0.1

Type RM Length L Ch R = 1 ,22279.9 ,548.4,545.1,540.7
XS GIS Cut Line= 4
     1680752.969      743637.071     1680772.501      743723.877
     1680839.775      744060.249     1680867.987      744364.068
#Sta/Elev= 30
       0 1047.33    17.8 1043.24    26.7 1041.45    44.5  1038.5    53.4 1037.18
    71.2  1035.1    80.1 1034.32    98.8 1033.15   108.6 1032.27   147.8 1027.89
   157.6 1027.37     187  1027.1   206.6 1027.16     236 1028.04   255.6 1028.15
   265.4 1027.44   274.2 1027.06     285 1026.96   289.2 1027.48   304.6 1029.56
   314.4 1030.34   324.2 1030.66     432 1032.25   527.4  1033.4   546.4 1033.88
   594.1 1035.79   622.7 1037.45   641.8 1039.01   670.4 1041.67   737.1 1048.56
#Mann= 3 , 0 , 0
       0     .06       0   255.6    .045       0   289.2     .06       0
Bank Sta=255.6,289.2
XS Rating Curve= 0 ,0
Exp/Cntr=0.3,0.1