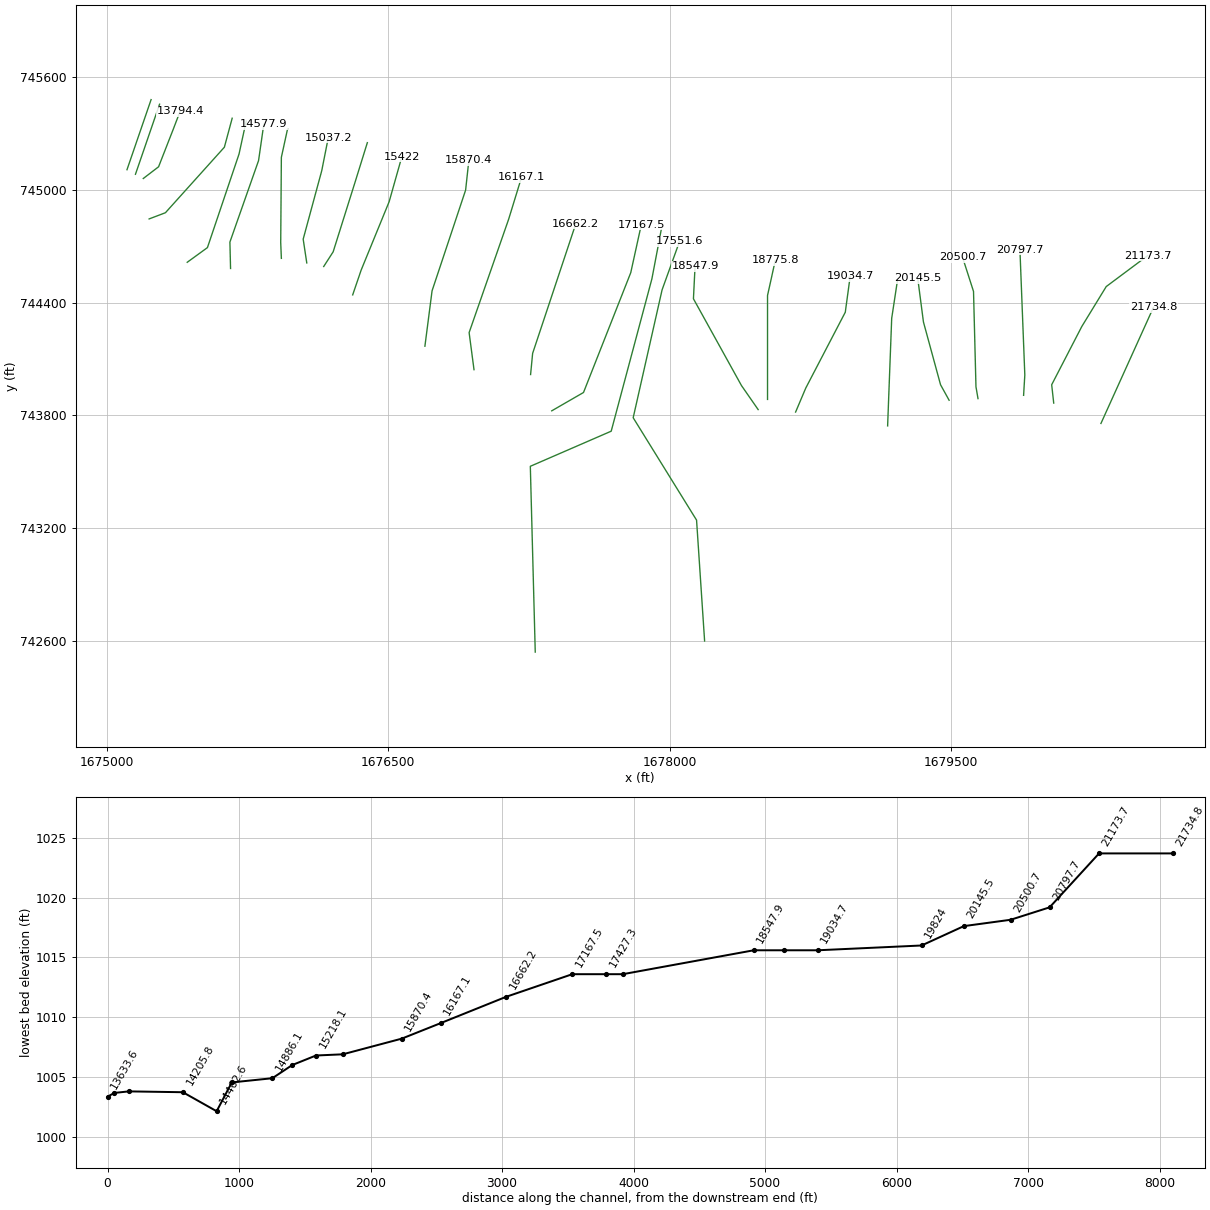
HEC-RAS study SFTOMLINRN.prj: SFTOMLINRN

--- SFTOMLINRN.g01 (geometry) --- (continued)

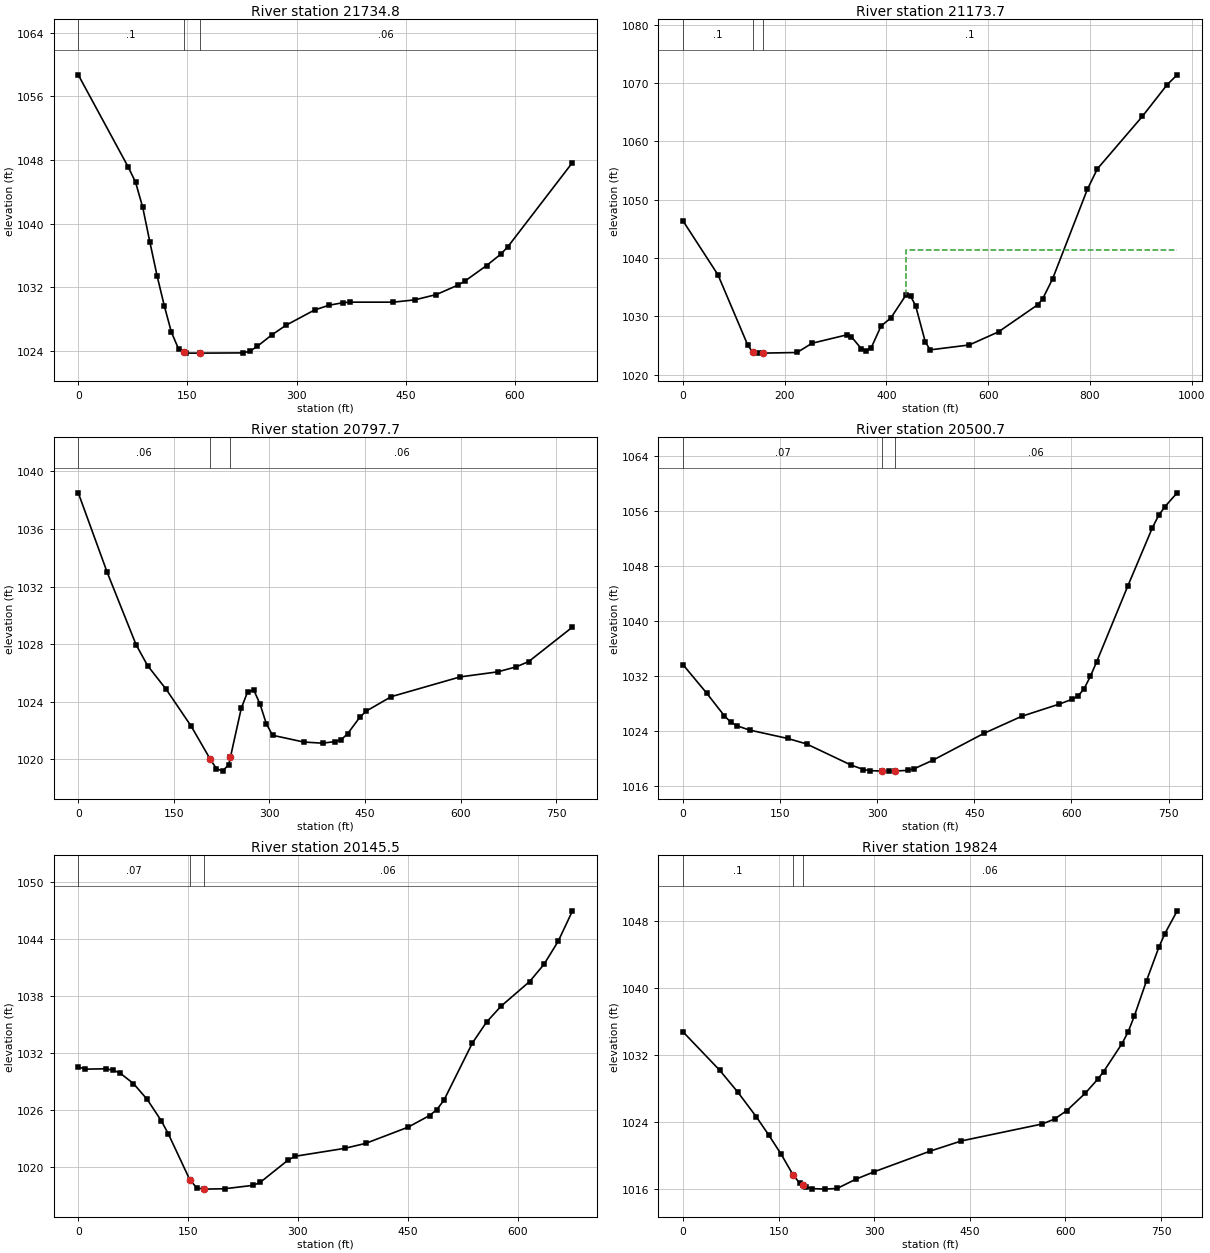
Type RM Length L Ch R = 1 ,21734.8 ,560,561.1,560.4
XS GIS Cut Line= 2
      1680299.41      743756.429     1680579.358      744374.919
#Sta/Elev= 30
       0  1058.7    68.9 1047.06    78.7  1045.2    88.6 1042.02    98.4 1037.66
   108.2 1033.46   118.1 1029.68   127.9 1026.35   137.8 1024.22   145.1 1023.83
   147.6  1023.7   167.3  1023.7   226.3 1023.73   236.1 1023.95     246 1024.56
   265.7 1025.98   285.3  1027.2   324.7 1029.13   344.4 1029.72     364 1030.05
   373.9 1030.11   432.9 1030.11   462.4  1030.4     492 1031.07   521.5 1032.25
   531.3 1032.77   560.8 1034.71   580.5 1036.15   590.3  1037.1   678.9 1047.67
#Mann= 3 , 0 , 0
       0      .1       0   145.1    .045       0   167.3     .06       0
Bank Sta=145.1,167.3
XS Rating Curve= 0 ,0
Exp/Cntr=0.3,0.1

Type RM Length L Ch R = 1 ,21173.7 ,347.2,376,386.3
XS GIS Cut Line= 5
     1680047.674      743864.936     1680036.824      743962.592
     1680197.414      744272.922     1680327.622      744485.596
     1680547.776      744649.731
#Sta/Elev= 30
       0 1046.39    68.8 1037.13   127.4 1025.07   137.1 1023.85   146.8  1023.7
   156.5  1023.7   224.4 1023.81   253.6 1025.39   321.5 1026.82   331.2  1026.5
   350.6 1024.46   360.3 1024.15     370  1024.6   389.4 1028.35   408.8 1029.74
     438 1033.61   447.7 1033.42   457.3 1031.85   476.4 1025.62     486 1024.26
   562.8  1025.1   620.3 1027.35     697 1031.97   706.8 1032.95   726.5 1036.41
   795.1 1051.81   814.7 1055.31     903 1064.29     952 1069.76   971.6 1071.43
#Mann= 3 , 0 , 0
       0      .1       0   137.1    .045       0   156.5      .1       0
#XS Ineff= 2 , 0
                          438.44         1041.35
Permanent Ineff=
       F       F
Bank Sta=137.1,156.5
XS Rating Curve= 0 ,0
Exp/Cntr=0.3,0.1

Type RM Length L Ch R = 1 ,20797.7 ,296.8,296.9,296.6
XS GIS Cut Line= 3
     1679887.084      743906.169     1679893.594      744014.676
     1679867.553      744680.908
#Sta/Elev= 30
       0 1038.51    45.3    1033    90.6 1027.98   108.7 1026.52   138.1 1024.86
   177.3  1022.3   206.8 1020.04   216.6 1019.37   226.4 1019.19   236.2 1019.65
   238.7 1020.15   255.8 1023.56   265.6 1024.68   275.4 1024.82   285.2 1023.84
     295 1022.49   304.8 1021.68   353.8 1021.21   383.2 1021.13   402.8 1021.24
   412.7 1021.38   422.5 1021.78   442.1 1022.95   451.9 1023.36   491.1 1024.36
     599 1025.73   657.8 1026.08   687.2 1026.43   706.8  1026.8   775.4 1029.19
#Mann= 3 , 0 , 0
       0     .06       0   206.8    .045       0   238.7     .06       0
Bank Sta=206.8,238.7
XS Rating Curve= 0 ,0
Exp/Cntr=0.3,0.1

Type RM Length L Ch R = 1 ,20500.7 ,350.2,355.2,350.6
XS GIS Cut Line= 4
     1679644.028      743888.808     1679633.178      743951.742
     1679620.157      744459.554     1679561.563      744641.846
#Sta/Elev= 30
       0 1033.66    36.5 1029.52    63.9 1026.21    73.6  1025.3    83.4 1024.75
   102.9 1024.13   161.6 1022.91   190.9 1022.11   259.2 1019.05   278.8 1018.38
   288.6 1018.22   308.1 1018.16   317.8 1018.15   327.6 1018.17   347.2 1018.26
   356.9 1018.49   386.2 1019.75   464.4 1023.63     523 1026.13   581.4 1027.92
   600.6  1028.6   610.1 1029.07   619.7 1030.18   629.3 1031.97   638.9 1034.07
   686.7 1045.04     725  1053.6   734.6 1055.38   744.2 1056.66   763.3 1058.68
#Mann= 3 , 0 , 0
       0     .07       0   308.1    .045       0   327.6     .06       0
Bank Sta=308.1,327.6
XS Rating Curve= 0 ,0
Exp/Cntr=0.3,0.1

Type RM Length L Ch R = 1 ,20145.5 ,328.1,321.6,276.8
XS GIS Cut Line= 4
     1679489.949      743880.127     1679444.376      743962.592
      1679353.23      744296.794     1679322.848      744528.999
#Sta/Elev= 30
       0 1030.52     9.4 1030.28    37.7 1030.32    47.1 1030.17    56.5  1029.9
    75.4 1028.76    94.2 1027.08   113.5 1024.82   123.1 1023.43   152.2 1018.63
   161.6 1017.77   171.2 1017.62   200.1 1017.66   238.6 1018.02   248.2 1018.32
   286.7  1020.7   296.3 1021.09   363.6 1021.92   392.5 1022.45   450.4 1024.16
   479.7 1025.39   489.4    1026   499.2 1026.99   538.2 1033.05   557.7 1035.27
   577.2 1036.92   616.3 1039.53   635.8 1041.33   655.3 1043.78   674.8 1046.99
#Mann= 3 , 0 , 0
       0     .07       0   152.2    .045       0   171.2     .06       0
Bank Sta=152.2,171.2
XS Rating Curve= 0 ,0
Exp/Cntr=0.3,0.1

Type RM Length L Ch R = 1 ,19824   ,798.7,789.3,737.3
XS GIS Cut Line= 4
     1679162.258      743743.408     1679166.598      743858.426
     1679183.959      744316.325     1679214.341      744515.978
#Sta/Elev= 30
       0 1034.76    57.6 1030.18    86.3 1027.54   115.1 1024.62   134.6 1022.45
   154.1 1020.15   172.8 1017.69   183.4 1016.69   187.8 1016.49   193.1 1016.24
   202.8 1016.07   222.3    1016   241.8 1016.08   271.1 1017.18   300.3 1018.08
   388.1 1020.54   436.8 1021.75   563.6 1023.77   582.9 1024.36   602.2 1025.37
     631 1027.43   650.3 1029.08   659.9 1030.02   688.7 1033.35   698.3 1034.75
     708 1036.63   727.2 1040.86   746.4 1044.82     756 1046.48   775.3 1049.19
#Mann= 3 , 0 , 0
       0      .1       0   172.8    .045       0   187.8     .06       0
Bank Sta=172.8,187.8
XS Rating Curve= 0 ,0
Exp/Cntr=0.3,0.1

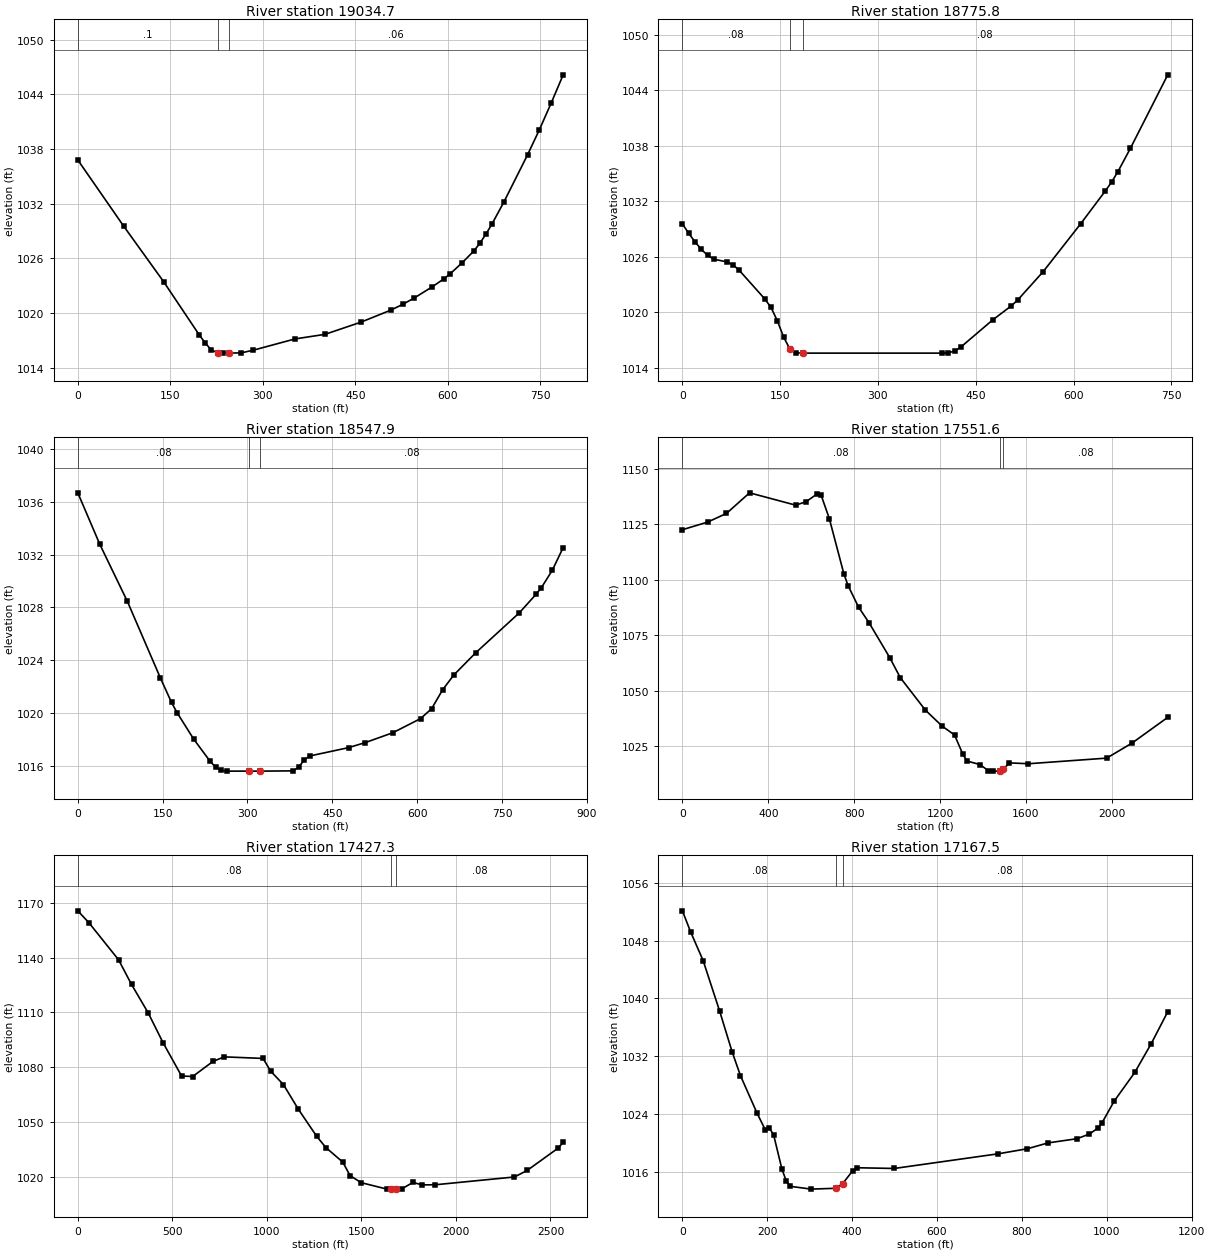
Type RM Length L Ch R = 1 ,19034.7 ,247.4,258.9,269.6
XS GIS Cut Line= 4
     1678671.806      743817.193      1678726.06      743945.231
     1678936.563      744348.877     1678962.605      744539.849
#Sta/Elev= 30
       0 1036.81    74.2 1029.56   139.1 1023.45   197.2 1017.57   206.9 1016.69
   216.6 1015.94   227.6 1015.63   235.9  1015.6   245.6  1015.6     265 1015.63
   284.4 1015.92   352.2 1017.16   400.6 1017.66   458.7 1018.99   507.1 1020.31
   526.5 1020.94   545.9 1021.67   574.9 1022.89   594.3 1023.79   603.9 1024.32
   623.2 1025.52   642.5 1026.84   652.1 1027.69   661.8 1028.67   671.4 1029.76
   690.7 1032.17   729.2 1037.37   748.5 1040.14   767.8  1043.1     787 1046.16
#Mann= 3 , 0 , 0
       0      .1       0   227.6    .045       0   245.6     .06       0
Bank Sta=227.6,245.6
XS Rating Curve= 0 ,0
Exp/Cntr=0.3,0.1

Type RM Length L Ch R = 1 ,18775.8 ,216,227.9,238.5
XS GIS Cut Line= 3
     1678522.067      743884.467     1678522.067      744437.853
     1678563.299      744624.485
#Sta/Elev= 30
       0 1029.57     9.7 1028.53    19.4 1027.62    29.1  1026.8    38.8 1026.16
    48.5 1025.74      68 1025.46    77.7 1025.14    87.4 1024.53   126.2 1021.47
   135.9 1020.54   145.6  1019.1   155.3 1017.34   164.8 1016.05   174.8 1015.63
   184.5  1015.6     398  1015.6   407.8 1015.63   417.5 1015.82   427.2 1016.26
   475.7 1019.17   504.8 1020.72   514.6 1021.36   553.4  1024.4   610.7 1029.55
     649 1033.14   658.5 1034.09   668.1 1035.21   687.2 1037.72   744.5 1045.66
#Mann= 3 , 0 , 0
       0     .08       0   164.8    .045       0   184.5     .08       0
Bank Sta=164.8,184.5
XS Rating Curve= 0 ,0
Exp/Cntr=0.3,0.1

Type RM Length L Ch R = 1 ,18547.9 ,955.1,996.3,974.8
XS GIS Cut Line= 4
     1678472.153      743830.214     1678383.178      743958.252
     1678127.101      744420.492     1678135.782      744594.103
#Sta/Elev= 30
       0 1036.68      39 1032.77    87.7 1028.45   146.2 1022.64   165.7  1020.8
   175.5 1020.03   204.8 1018.03   234.2 1016.33     244 1015.88   253.8 1015.65
   263.6  1015.6   302.7  1015.6   322.3  1015.6     381 1015.62   390.8 1015.91
   400.6 1016.47   410.4 1016.75   478.8 1017.38   508.2 1017.76   557.1 1018.51
   606.1 1019.58   625.6 1020.33   645.2 1021.77   664.8 1022.88   703.7 1024.57
   780.9  1027.6   809.9 1028.98   819.6 1029.49   838.9 1030.81   858.2 1032.53
#Mann= 3 , 0 , 0
       0     .08       0   302.7    .045       0   322.3     .08       0
Bank Sta=302.7,322.3
XS Rating Curve= 0 ,0
Exp/Cntr=0.3,0.1

Type RM Length L Ch R = 1 ,17551.6 ,140.3,124.3,121.4
XS GIS Cut Line= 5
     1678186.664      742597.647      1678143.79      743241.411
     1677805.921      743786.811     1677960.001      744468.235
     1678053.317      744726.481
#Sta/Elev= 30
       0  1122.6   117.3 1126.04   205.3 1129.96   312.8 1139.26   527.9 1133.68
   576.8  1135.3   625.6 1138.65   645.2 1138.42   684.1 1127.64   752.1 1102.63
   771.6 1097.35   820.2 1087.68   868.8 1080.66     966 1064.78  1014.6 1055.81
  1131.2 1041.18    1209 1033.96  1267.3 1029.91  1306.4 1021.12  1326.1 1018.13
  1385.2 1016.58  1424.5 1013.82  1444.2  1013.6  1477.9 1013.65  1493.4 1014.43
  1522.9 1017.32  1611.5 1016.94  1975.6 1019.47  2093.3 1026.24    2260 1037.88
#Mann= 3 , 0 , 0
       0     .08       0  1477.9    .045       0  1493.4     .08       0
Bank Sta=1477.9,1493.4
XS Rating Curve= 0 ,0
Exp/Cntr=0.3,0.1

Type RM Length L Ch R = 1 ,17427.3 ,230.5,259.8,256.9
XS GIS Cut Line= 5
     1677283.887      742538.619      1677257.62      743528.191
     1677688.733      743715.196     1677905.747      744526.828
      1677955.66      744789.415
#Sta/Elev= 30
       0 1165.47    58.8 1158.96   215.6 1138.75   284.2 1125.28   372.4 1109.76
   450.8 1093.51   548.9 1075.33   607.7 1075.06   715.5 1083.33   774.3 1085.78
   980.1 1084.92  1019.3 1078.06  1087.8 1070.63  1166.1 1057.26    1264 1042.34
    1313 1036.19  1401.1  1028.4  1440.3 1020.98  1498.9 1017.12  1635.7  1013.6
  1655.2  1013.6  1684.5  1013.6  1713.8 1013.75  1772.5 1017.25  1821.3 1015.92
  1889.7 1015.97  2309.5 1020.23  2376.4 1023.77  2538.6 1035.83  2567.3 1039.06
#Mann= 3 , 0 , 0
       0     .08       0  1655.2    .045       0  1684.5     .08       0
Bank Sta=1655.2,1684.5
XS Rating Curve= 0 ,0
Exp/Cntr=0.3,0.1

Type RM Length L Ch R = 1 ,17167.5 ,535.3,505.3,503.4
XS GIS Cut Line= 4
     1677371.893      743823.703     1677541.164       743921.36
       1677792.9       744559.38     1677849.324      744815.457
#Sta/Elev= 30
       0 1052.12    19.5 1049.19    48.9 1045.23    87.9 1038.22   117.2  1032.6
   136.8 1029.31   175.9 1024.12   195.4 1021.79   205.2 1022.05     215  1021.1
   234.6 1016.34   244.4 1014.79   254.2 1013.99   303.2  1013.6   362.7 1013.72
   377.7 1014.37   401.2 1016.14     411 1016.56   499.2 1016.46   744.1 1018.49
   812.7 1019.19   861.7    1020   929.9 1020.58     959 1021.23   978.4 1022.02
   988.1 1022.72  1017.3 1025.78  1065.8 1029.75  1104.7 1033.75  1143.5 1038.15
#Mann= 3 , 0 , 0
       0     .08       0   362.7    .045       0   377.7     .08       0
Bank Sta=362.7,377.7
XS Rating Curve= 0 ,0
Exp/Cntr=0.3,0.1

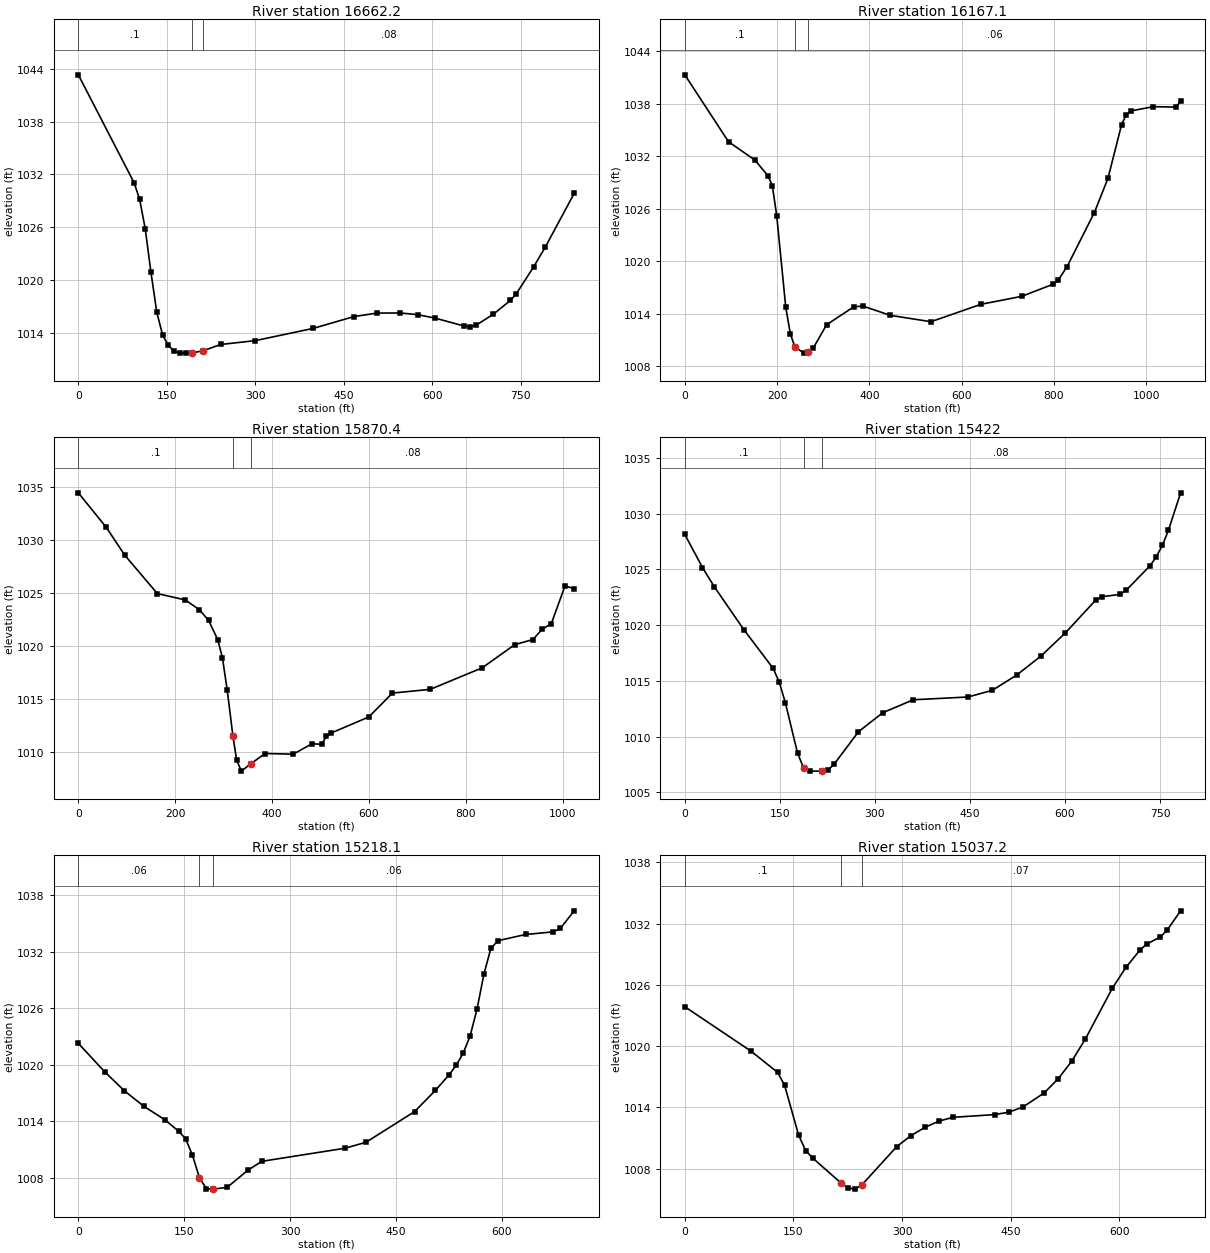
Type RM Length L Ch R = 1 ,16662.2 ,494,495.1,492.4
XS GIS Cut Line= 3
     1677259.046      744016.846     1677269.896      744129.693
     1677499.931      744819.797
#Sta/Elev= 30
       0 1043.31    94.5 1031.06   103.9 1029.19   113.4 1025.85   123.2 1020.86
     133 1016.35   142.9 1013.76   152.7 1012.57   162.5  1011.9   172.4 1011.71
   182.2  1011.7     192 1011.72   211.7 1011.97   241.2 1012.68   300.1 1013.12
   398.4 1014.51   467.2 1015.85   506.6 1016.25   545.9 1016.26   575.4 1016.07
   604.9 1015.68     654 1014.78   663.9 1014.69   673.7 1014.84   703.2 1016.09
   732.7 1017.69   742.5 1018.42     772 1021.49   791.6 1023.71   840.8 1029.84
#Mann= 3 , 0 , 0
       0      .1       0     192    .045       0   211.7     .08       0
Bank Sta=192,211.7
XS Rating Curve= 0 ,0
Exp/Cntr=0.3,0.1

Type RM Length L Ch R = 1 ,16167.1 ,295.5,296.7,298.4
XS GIS Cut Line= 4
     1676957.396      744042.887     1676931.355       744240.37
     1677141.858      744843.669     1677211.303      745069.363
#Sta/Elev= 30
       0 1041.32    94.8 1033.67   151.8 1031.58   180.2 1029.78   189.7 1028.64
   199.2  1025.2   218.8 1014.73   228.7 1011.71   238.5 1010.22   258.2 1009.51
     268 1009.61   277.8 1010.04   307.3 1012.76   366.3 1014.81     386 1014.89
     445 1013.83   533.4  1013.1   641.6 1015.09     730    1016   798.8  1017.4
   808.7 1017.82   828.3  1019.4   887.4 1025.58   916.9 1029.49   946.4 1035.64
   956.2 1036.72   966.1 1037.19  1015.3 1037.68  1064.5 1037.63  1074.3 1038.32
#Mann= 3 , 0 , 0
       0      .1       0   238.5    .045       0     268     .06       0
Bank Sta=238.5,268
XS Rating Curve= 0 ,0
Exp/Cntr=0.3,0.1

Type RM Length L Ch R = 1 ,15870.4 ,447.1,448.4,446.5
XS GIS Cut Line= 4
     1676695.678      744167.887     1676733.872      744463.026
     1676912.692      744999.485     1676930.053      745159.207
#Sta/Elev= 30
       0 1034.45    57.6  1031.2      96 1028.56   163.2 1024.95   220.8 1024.35
   249.6 1023.44   268.8 1022.43     288 1020.59   297.6 1018.87   307.4 1015.85
   319.2  1011.5   326.8 1009.26   336.6 1008.21   356.1  1008.9   385.4 1009.87
   443.8 1009.81   482.8  1010.8   502.3 1010.73   512.1 1011.49   521.8  1011.8
   599.8 1013.32   648.6 1015.57   726.6 1015.92   833.8 1017.95   900.9 1020.13
   938.7 1020.62   957.6 1021.59   976.5 1022.11  1004.8 1025.67  1023.7 1025.42
#Mann= 3 , 0 , 0
       0      .1       0   319.2    .045       0   356.1     .08       0
Bank Sta=319.2,356.1
XS Rating Curve= 0 ,0
Exp/Cntr=0.3,0.1

Type RM Length L Ch R = 1 ,15422   ,204,203.9,204.5
XS GIS Cut Line= 4
     1676310.695      744441.325     1676355.834      744573.269
      1676505.14      744937.853     1676572.848      745177.436
#Sta/Elev= 30
       0 1028.13    27.9 1025.16    46.5 1023.44      93  1019.6   139.4 1016.12
   149.1 1014.88   158.7 1013.03   177.9 1008.52   187.6 1007.16   197.1  1006.9
   216.3  1006.9   225.9    1007   235.5 1007.51     274 1010.43   312.4 1012.14
   360.5  1013.3   446.9 1013.55   485.4 1014.15   523.8 1015.52   562.2 1017.23
   600.4 1019.29   648.3 1022.23   657.9 1022.54   686.6 1022.75   696.2 1023.11
   734.5 1025.34   744.1 1026.13   753.7 1027.16   763.2 1028.51   782.4 1031.86
#Mann= 3 , 0 , 0
       0      .1       0   187.6    .045       0   216.3     .08       0
Bank Sta=187.6,216.3
XS Rating Curve= 0 ,0
Exp/Cntr=0.3,0.1

Type RM Length L Ch R = 1 ,15218.1 ,179.9,180.9,181.4
XS GIS Cut Line= 4
     1676156.181      744592.367     1676206.528      744670.492
     1676324.584      745045.492      1676388.82      745252.089
#Sta/Elev= 30
       0 1022.26    37.2 1019.26    65.1 1017.24    92.9 1015.58   122.4 1014.17
   142.1 1012.94   151.9 1012.15   161.7 1010.39   171.6 1007.99   181.4 1006.85
   191.2  1006.8   210.9 1006.99   240.4 1008.82     260 1009.75     378 1011.14
   407.5 1011.77   476.3 1015.02   505.8 1017.27   525.4 1018.94   535.3 1019.94
   545.1 1021.21   554.9 1023.02   564.8 1025.89   574.6 1029.62   584.4 1032.33
   594.3 1033.15   633.6 1033.81   672.9 1034.09   682.8 1034.45   702.4 1036.32
#Mann= 3 , 0 , 0
       0     .06       0   171.6    .045       0   191.2     .06       0
Bank Sta=171.6,191.2
XS Rating Curve= 0 ,0
Exp/Cntr=0.3,0.1

Type RM Length L Ch R = 1 ,15037.2 ,146.8,151,156.6
XS GIS Cut Line= 4
     1676065.903      744611.464     1676046.806        744738.2
     1676145.765      745102.783     1676180.487       745278.13
#Sta/Elev= 30
       0 1023.86    91.6  1019.5   128.2 1017.43   137.8 1016.17   157.2 1011.28
   166.9 1009.78   176.6 1009.04   215.4 1006.62     225 1006.13   234.7    1006
   244.6 1006.42   292.8 1010.17   312.2 1011.23   331.6 1012.05     351 1012.66
   370.3 1013.03   428.4  1013.3   447.8 1013.54   467.2 1014.05   496.3 1015.42
   515.4 1016.79   534.2 1018.51     553 1020.68   590.6  1025.7   609.4 1027.73
   628.2 1029.38   637.6 1029.99   656.5 1030.68   665.9 1031.35   684.7 1033.25
#Mann= 3 , 0 , 0
       0      .1       0   215.4    .045       0   244.6     .07       0
Bank Sta=215.4,244.6
XS Rating Curve= 0 ,0
Exp/Cntr=0.3,0.1

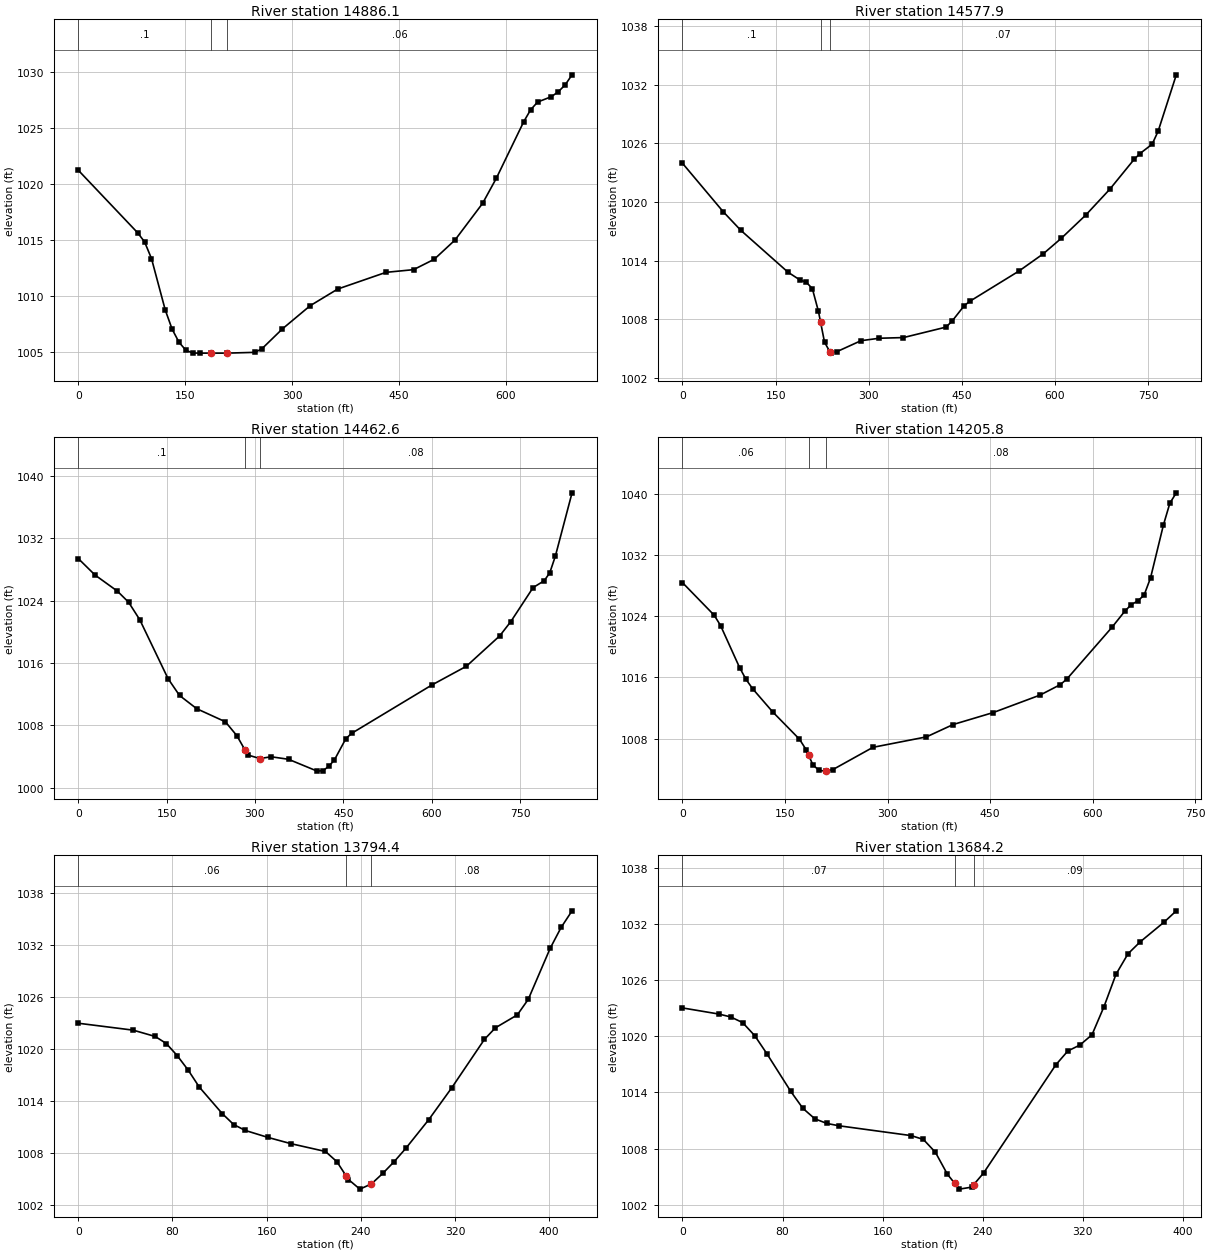
Type RM Length L Ch R = 1 ,14886.1 ,312.7,308.2,301.2
XS GIS Cut Line= 4
     1675930.487      744635.769     1675927.015      744719.103
     1675930.487      745173.964     1675963.473      745325.005
#Sta/Elev= 30
       0 1021.23    83.4 1015.64    93.1 1014.83   102.8 1013.34   122.1 1008.75
   131.8 1007.03   141.5 1005.86   151.2 1005.15   160.8 1004.91   170.5  1004.9
   186.8  1004.9   209.2  1004.9   247.9 1004.97   257.6 1005.28   286.6 1007.07
   325.4 1009.13   364.1 1010.62   431.8 1012.11   470.5 1012.35   499.6 1013.28
   528.6 1014.99   567.3 1018.26   586.6  1020.5   625.2 1025.57   634.9 1026.63
   644.6 1027.31   663.9 1027.79   673.6 1028.23   683.2 1028.84   692.9 1029.74
#Mann= 3 , 0 , 0
       0      .1       0   186.8    .045       0   209.2     .06       0
Bank Sta=186.8,209.2
XS Rating Curve= 0 ,0
Exp/Cntr=0.3,0.1

Type RM Length L Ch R = 1 ,14577.9 ,115.7,115.3,114.8
XS GIS Cut Line= 4
     1675659.653       744581.95     1675656.181      744722.575
     1675808.959      745156.603     1675836.737      745349.311
#Sta/Elev= 30
       0 1023.95    65.6    1019    93.8 1017.11     170 1012.82   189.6 1012.01
   199.4  1011.8   209.2 1011.14     219 1008.82   222.4 1007.73   228.8 1005.67
   237.4 1004.69   238.6 1004.55   248.4 1004.69   287.5 1005.82   316.9 1006.07
     356 1006.14   424.6 1007.21   434.4 1007.83     454 1009.41   463.7 1009.88
   542.1 1012.94   581.2  1014.7   610.5  1016.3   649.5 1018.65   688.4  1021.3
   727.4 1024.34   737.1 1024.95   756.6  1025.9   766.3 1027.24   795.5 1032.99
#Mann= 3 , 0 , 0
       0      .1       0   222.4    .045       0   237.4     .07       0
Bank Sta=222.4,237.4
XS Rating Curve= 0 ,0
Exp/Cntr=0.3,0.1

Type RM Length L Ch R = 1 ,14462.6 ,265.7,256.8,247.4
XS GIS Cut Line= 4
     1675428.751      744614.936      1675536.39      744693.061
     1675704.792      745191.325     1675742.987      745366.672
#Sta/Elev= 30
       0 1029.43    28.5 1027.31    66.5 1025.24    85.5 1023.82   104.5 1021.57
   152.5 1014.01     172 1011.85   201.2 1010.15   249.9 1008.47   269.4 1006.68
   282.7 1004.91   288.8 1004.19   308.3 1003.76   327.8 1003.98     357 1003.66
   405.7 1002.14   415.5  1002.2   425.2 1002.74   434.9 1003.57   454.4 1006.31
   464.2 1006.99   600.5  1013.2     659  1015.6   715.6  1019.5   734.5 1021.34
   772.3  1025.7   791.2 1026.58   800.6  1027.6   810.1 1029.74   838.4 1037.86
#Mann= 3 , 0 , 0
       0      .1       0   282.7    .045       0   308.3     .08       0
Bank Sta=282.7,308.3
XS Rating Curve= 0 ,0
Exp/Cntr=0.3,0.1

Type RM Length L Ch R = 1 ,14205.8 ,401.3,411.5,420.7
XS GIS Cut Line= 4
     1675225.626      744845.839     1675312.431      744878.825
     1675626.667      745227.783     1675668.334      745382.297
#Sta/Elev= 30
       0 1028.43    46.4 1024.16    55.7 1022.81    83.6 1017.29    92.9 1015.76
   102.6 1014.53     132 1011.49   171.1 1007.92   180.9 1006.54   184.6  1005.8
   190.7 1004.57   199.6 1003.83   210.3 1003.73     220 1003.93   278.7 1006.85
     357 1008.22   396.1 1009.84   454.8 1011.41   523.3  1013.7   552.7 1015.06
   562.4  1015.8   628.4 1022.58   647.2 1024.69   656.6 1025.55     666 1026.02
   675.4  1026.8   684.8 1029.05   703.7    1036   713.1 1038.85   722.5  1040.2
#Mann= 3 , 0 , 0
       0     .06       0   184.6    .045       0   210.3     .08       0
Bank Sta=184.6,210.3
XS Rating Curve= 0 ,0
Exp/Cntr=0.3,0.1

Type RM Length L Ch R = 1 ,13794.4 ,109.3,110.1,111.2
XS GIS Cut Line= 4
     1675194.376      745061.117     1675275.973      745123.617
     1675354.098      745323.269     1675390.556      745418.755
#Sta/Elev= 30
       0 1022.93    46.7 1022.13    65.4  1021.4    74.8 1020.59    84.1 1019.19
    93.4 1017.52   102.8 1015.57   122.3 1012.51     132 1011.25   141.8 1010.57
   161.2 1009.76   180.7 1009.04     210 1008.14   219.7 1006.96   227.4 1005.35
   229.5 1004.91   239.2  1003.8     249  1004.4   258.7 1005.62   268.4 1006.98
   278.2  1008.5   297.7 1011.81   317.2 1015.48     345 1021.07   354.3  1022.4
   372.9 1023.89   382.2 1025.68   400.8 1031.56   410.1 1033.97   419.4 1035.89
#Mann= 3 , 0 , 0
       0     .06       0   227.4    .045       0     249     .08       0
Bank Sta=227.4,249
XS Rating Curve= 0 ,0
Exp/Cntr=0.3,0.1

Type RM Length L Ch R = 1 ,13684.2 ,50.9,50.7,50.7
XS GIS Cut Line= 2
     1675152.709      745083.686     1675281.181       745456.95
#Sta/Elev= 30
       0 1023.04    28.9 1022.39    38.5 1022.08    48.1 1021.47    57.8 1020.07
    67.4 1018.16    86.6 1014.11    96.3  1012.3   105.9 1011.18   115.5 1010.69
   125.2 1010.44   182.9 1009.39   192.6 1008.98   202.2 1007.61   211.8 1005.26
   217.7 1004.28   221.4 1003.67   231.1 1003.88   232.7 1004.13   240.7 1005.39
   298.5 1016.96   308.1 1018.44   317.7 1019.07   327.4 1020.17     337 1023.18
   346.6 1026.64   356.2 1028.83   365.9  1030.1   385.1 1032.22   394.8 1033.42
#Mann= 3 , 0 , 0
       0     .07       0   217.7    .045       0   232.7     .09       0
Bank Sta=217.7,232.7
XS Rating Curve= 0 ,0
Exp/Cntr=0.3,0.1

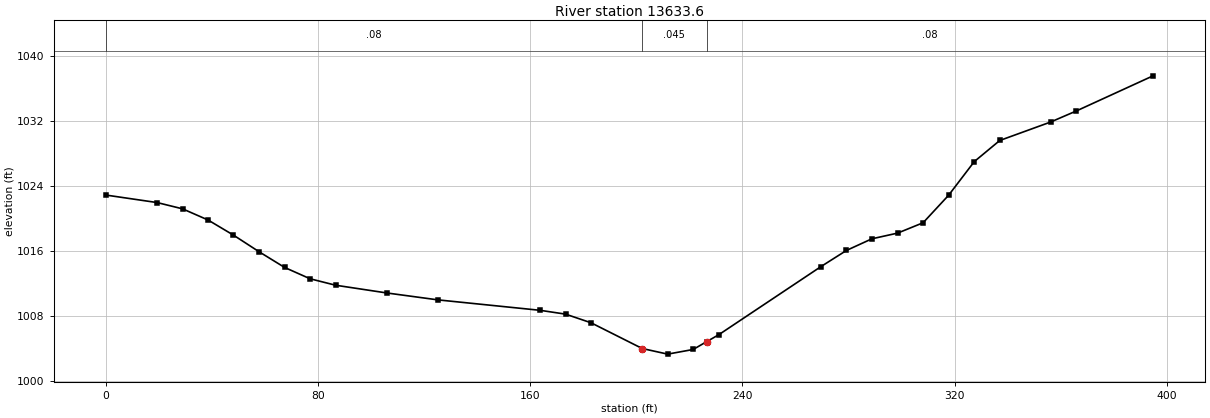
Type RM Length L Ch R = 1 ,13633.6 ,109.7,116.9,123.8
XS GIS Cut Line= 2
      1675107.57      745107.992     1675236.042      745481.255
#Sta/Elev= 30
       0 1022.89    19.3 1021.97    28.9  1021.2    38.5 1019.83    48.1 1017.97
    57.8 1015.92    67.4    1014      77 1012.61    86.6 1011.82   105.9 1010.87
   125.2 1010.02   163.7 1008.74   173.3 1008.27   182.9 1007.21   202.2 1004.05
   211.8 1003.36   221.4 1003.93   226.5 1004.89   231.1 1005.75   269.6 1014.11
   279.2 1016.09   288.8 1017.52   298.5 1018.22   308.1 1019.49   317.7 1022.86
   327.4    1027     337 1029.59   356.2 1031.86   365.9 1033.22   394.8 1037.53
#Mann= 3 , 0 , 0
       0     .08       0   202.2    .045       0   226.5     .08       0
Bank Sta=202.2,226.5
XS Rating Curve= 0 ,0
Exp/Cntr=0.3,0.1