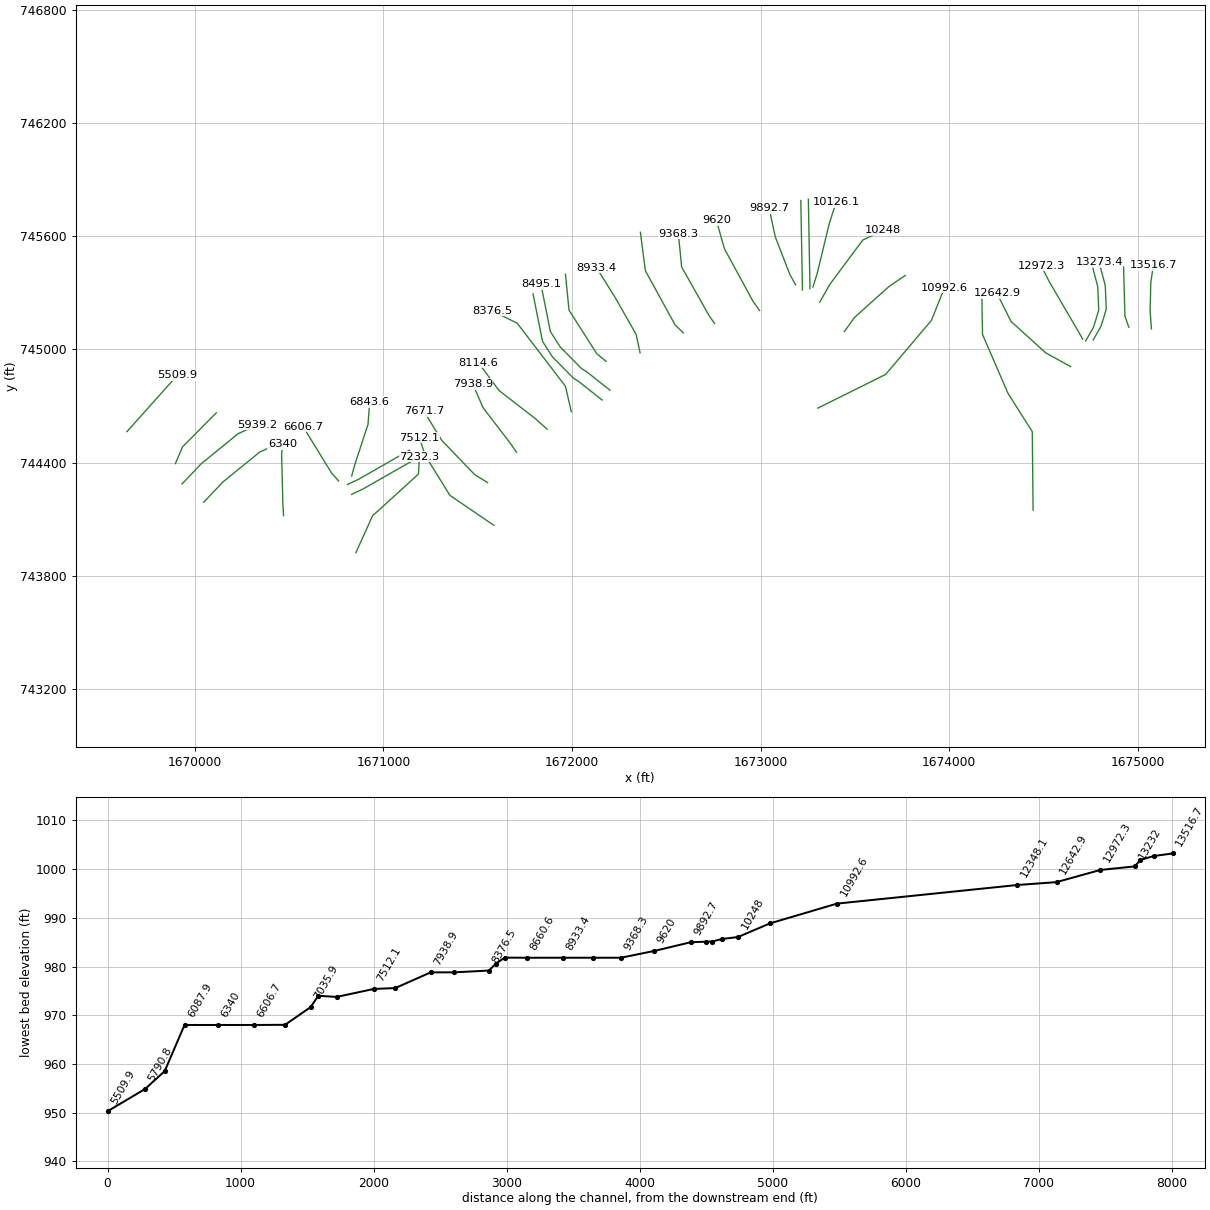
HEC-RAS study SFTOMLINRN.prj: SFTOMLINRN

--- SFTOMLINRN.g01 (geometry) --- (continued)

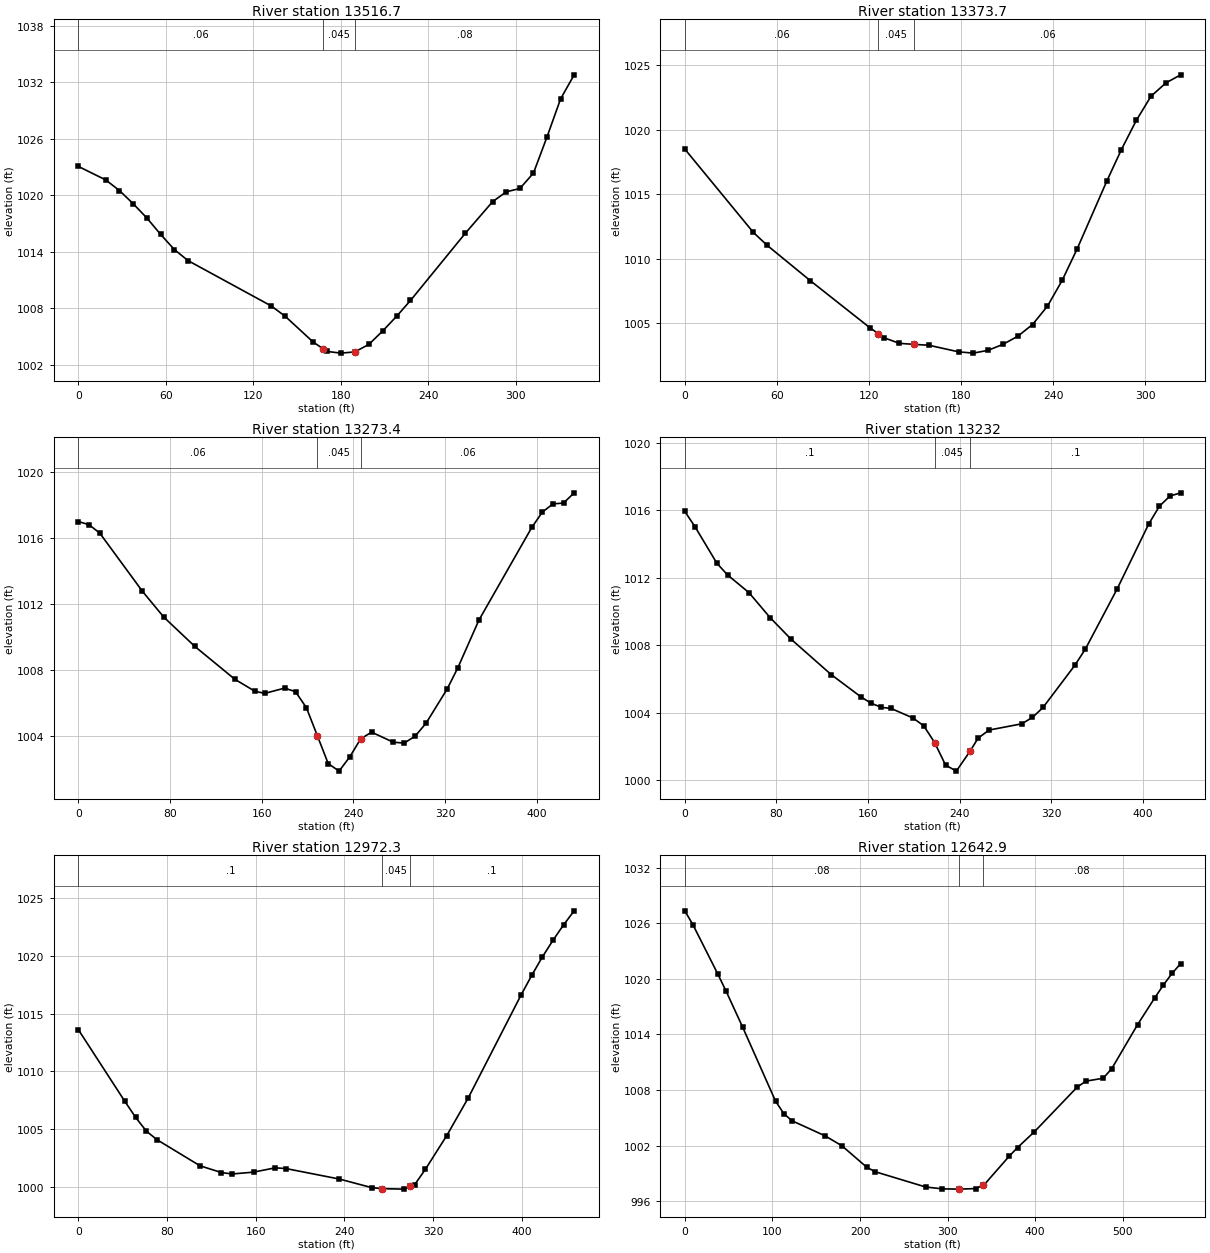
Type RM Length L Ch R = 1 ,13516.7 ,141.8,143,144.1
XS GIS Cut Line= 4
     1675072.848      745107.992     1675065.903      745201.742
     1675069.376      745354.519     1675083.265      745446.533
#Sta/Elev= 27
       0 1023.07    18.8 1021.63    28.2  1020.5    37.6  1019.1      47 1017.58
    56.4 1015.84    65.8 1014.23    75.2 1013.05   132.2 1008.23   141.8 1007.13
   160.9  1004.4   167.9 1003.66   170.4 1003.39     180 1003.21   189.5 1003.34
   199.1 1004.13   208.6 1005.56   218.2 1007.13   227.7 1008.81   265.4 1015.98
     284 1019.32   293.4 1020.37   302.7 1020.72     312 1022.36   321.3 1026.21
   330.6 1030.25   339.9 1032.81
#Mann= 3 , 0 , 0
       0     .06       0   167.9    .045       0   189.5     .08       0
Bank Sta=167.9,189.5
XS Rating Curve= 0 ,0
Exp/Cntr=0.3,0.1

Type RM Length L Ch R = 1 ,13373.7 ,100,100.4,100.9
XS GIS Cut Line= 3
     1674953.056      745116.672     1674932.223        745175.7
     1674925.278      745436.117
#Sta/Elev= 25
       0 1018.51    44.7 1012.04    53.6 1011.05    81.9 1008.29   120.5 1004.66
     126  1004.2   130.1 1003.86   139.8 1003.44   149.4 1003.36   159.1 1003.29
   178.4 1002.78     188 1002.68   197.7  1002.9   207.3 1003.36     217 1003.99
   226.6  1004.9   236.3 1006.32   245.9 1008.32   255.6 1010.75   274.9    1016
   284.5 1018.47   294.2 1020.73   303.8 1022.61   313.5 1023.64   323.1 1024.27
#Mann= 3 , 0 , 0
       0     .06       0     126    .045       0   149.4     .06       0
Bank Sta=126,149.4
XS Rating Curve= 0 ,0
Exp/Cntr=0.3,0.1

Type RM Length L Ch R = 1 ,13273.4 ,41.6,41.4,41.6
XS GIS Cut Line= 6
      1674763.82      745048.964     1674805.487       745121.88
     1674821.112      745172.228     1674833.265      745213.894
     1674828.056      745337.158      1674795.07      745462.158
#Sta/Elev= 30
       0 1017.01     9.3 1016.82    18.7 1016.31      56 1012.78    74.6 1011.22
   101.6 1009.45   136.7 1007.45   154.1 1006.73   162.7  1006.6   180.1 1006.92
   189.6  1006.7   199.1 1005.73   208.6 1004.04   218.1 1002.35   227.6 1001.89
     237 1002.76   246.5 1003.85     256 1004.25     275 1003.64   284.5 1003.59
     294 1004.01   303.5 1004.79   321.9 1006.86   331.2 1008.14   349.6 1011.03
   395.8 1016.65     405 1017.58   414.3 1018.08   423.5 1018.13   432.8 1018.75
#Mann= 3 , 0 , 0
       0     .06       0   208.6    .045       0   246.5     .06       0
Bank Sta=208.6,246.5
XS Rating Curve= 0 ,0
Exp/Cntr=0.3,0.1

Type RM Length L Ch R = 1 ,13232   ,248.1,259.7,270.3
XS GIS Cut Line= 6
      1674723.89      745043.755     1674765.556      745116.672
     1674781.181      745167.019     1674793.334      745208.686
     1674788.126       745331.95      1674755.14       745456.95
#Sta/Elev= 30
       0 1015.93     9.3 1014.98      28 1012.86    37.3 1012.17      56 1011.12
    74.6 1009.63    92.8 1008.36   127.9 1006.26   154.1 1004.93   162.7 1004.57
   171.4 1004.33   180.1 1004.26   199.1  1003.7   208.6 1003.23   218.1 1002.24
   227.6 1000.91     237 1000.55     249 1001.73     256  1002.5   265.5 1002.98
     294 1003.35   303.5 1003.73   312.7 1004.32   340.4 1006.81   349.6 1007.77
   377.4 1011.34     405 1015.19   414.3 1016.24   423.5 1016.84   432.8 1017.03
#Mann= 3 , 0 , 0
       0      .1       0   218.1    .045       0     249      .1       0
Bank Sta=218.1,249
XS Rating Curve= 0 ,0
Exp/Cntr=0.3,0.1

Type RM Length L Ch R = 1 ,12972.3 ,322.3,329.4,335.4
XS GIS Cut Line= 4
     1674708.265      745054.172     1674687.431       745090.63
     1674531.181      745357.992     1674487.778      745443.061
#Sta/Elev= 26
       0 1013.61      42  1007.4    51.7 1006.02    61.4 1004.83      71 1004.09
   109.7 1001.84   129.1 1001.25   138.8 1001.13   158.1 1001.29   177.5 1001.66
   187.2  1001.6   235.5 1000.69   264.6  999.95   274.2  999.86   293.6  999.82
   299.4 1000.05   303.3  1000.2     313 1001.53   332.3 1004.45   351.7 1007.71
   399.4 1016.62     409 1018.31   418.5 1019.89   428.1 1021.33   437.6 1022.66
   447.2 1023.88
#Mann= 3 , 0 , 0
       0      .1       0   274.2    .045       0   299.4      .1       0
Bank Sta=274.2,299.4
XS Rating Curve= 0 ,0
Exp/Cntr=0.3,0.1

Type RM Length L Ch R = 1 ,12642.9 ,305.9,294.8,263
XS GIS Cut Line= 4
     1674644.028      744908.339     1674512.084      744981.255
     1674328.056      745147.922     1674253.403      745297.228
#Sta/Elev= 30
       0 1027.34     9.4 1025.82    37.7 1020.52    47.1 1018.68      66  1014.8
   103.6 1006.81   113.1 1005.45   122.5 1004.69   160.3 1003.06   179.4 1001.99
     208  999.66   217.6  999.19   274.9  997.55     294  997.35   313.1  997.32
   332.2  997.38   340.4  997.73   341.7  997.79   370.4 1000.88   379.9 1001.81
     399  1003.5   448.1 1008.34     458 1008.97   477.6 1009.28   487.4 1010.32
   516.9 1015.07   536.5 1017.96   546.3 1019.33   556.1 1020.58     566 1021.64
#Mann= 3 , 0 , 0
       0     .08       0   313.1    .045       0   340.4     .08       0
Bank Sta=313.1,340.4
XS Rating Curve= 0 ,0
Exp/Cntr=0.3,0.1

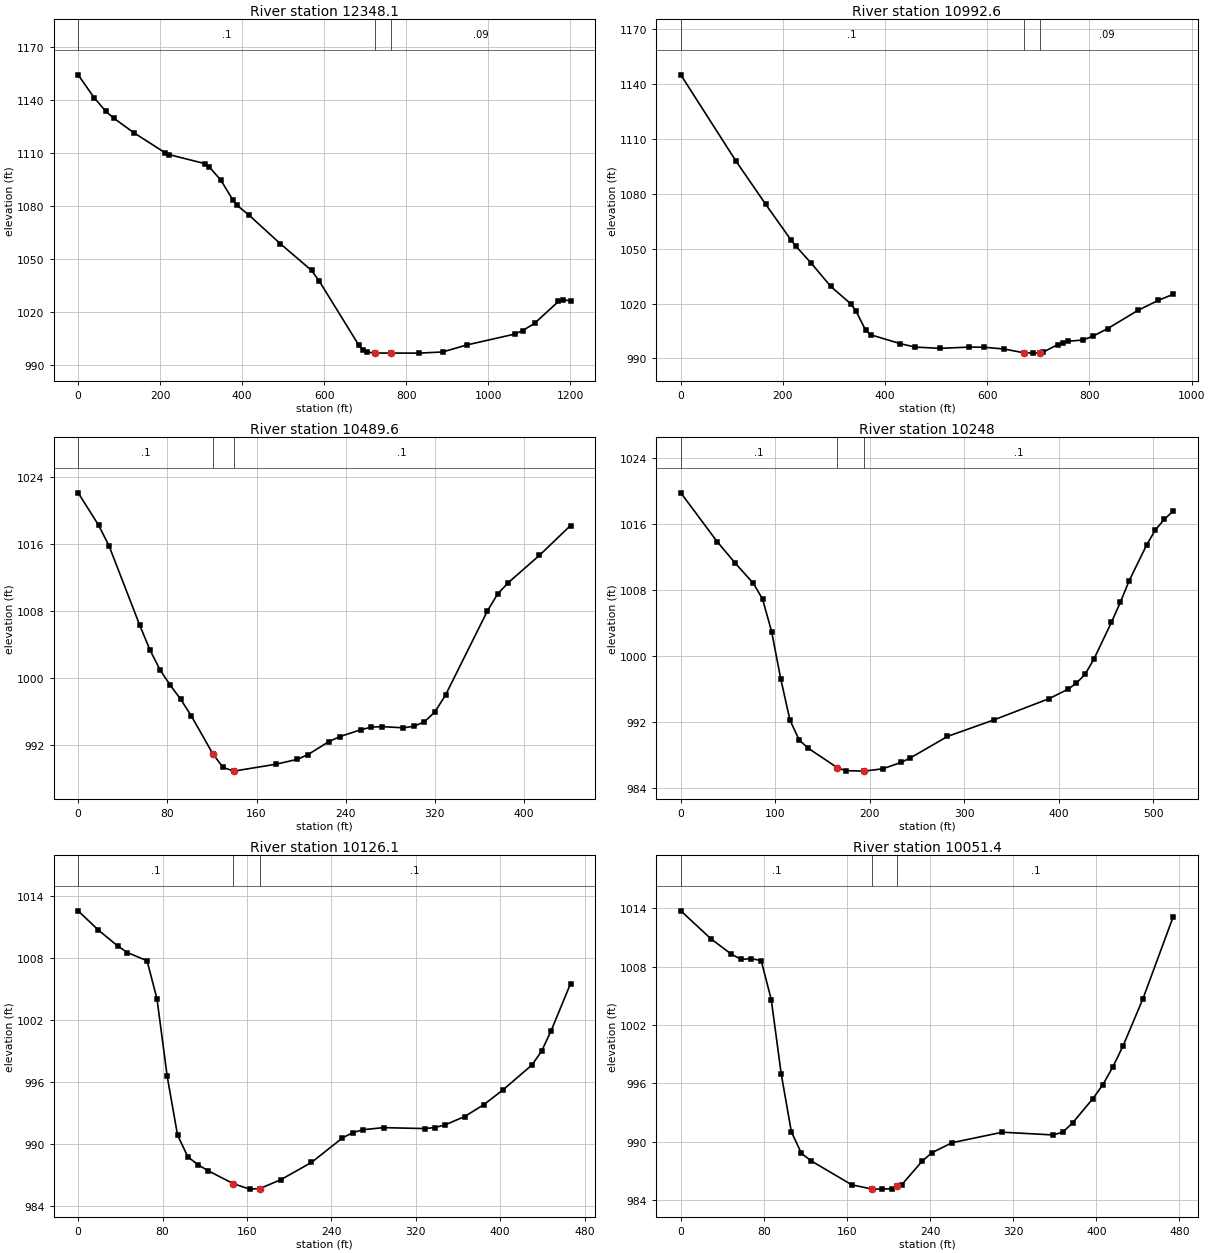
Type RM Length L Ch R = 1 ,12348.1 ,1380.2,1355.4,1347.4
XS GIS Cut Line= 5
     1674445.345       744147.85     1674440.869      744563.843
     1674312.431      744765.978     1674177.015      745078.478
     1674173.542      745283.339
#Sta/Elev= 30
       0 1154.18    38.7 1141.31    67.7 1133.46    87.1 1129.62   135.4 1121.49
   212.8 1109.99   222.5    1109   309.6 1103.92   319.3 1102.24   348.3  1094.5
   377.3 1083.41     387 1080.46     416 1074.96   492.6 1058.75   569.3 1043.52
   588.4 1037.37   684.7 1001.18   694.4  998.54   704.2  997.35   723.6  996.79
   762.5  996.78   830.7  996.73     889  997.38   947.4 1001.32  1064.4 1007.47
  1083.9 1009.43  1113.2 1013.56  1171.7 1025.99  1181.5 1026.86    1201  1026.4
#Mann= 3 , 0 , 0
       0      .1       0   723.6    .045       0   762.5     .09       0
Bank Sta=723.6,762.5
XS Rating Curve= 0 ,0
Exp/Cntr=0.3,0.1

Type RM Length L Ch R = 1 ,10992.6 ,506.9,503,357.9
XS GIS Cut Line= 4
     1673303.852      744688.214     1673663.126      744866.672
     1673906.181       745153.13     1673975.626      745326.742
#Sta/Elev= 30
       0 1144.84   107.6 1097.92   166.3  1074.1   215.2 1054.89     225 1051.36
   254.4 1042.31   293.5 1029.35   332.7 1019.82   342.4 1016.15     362 1005.36
   371.8 1002.92     430  998.05     459   996.2   507.1  995.53   564.9   996.2
   593.8  996.12   632.3  995.17   670.9  993.14   690.1  992.91     703  993.11
   709.4  993.49   738.3   997.6   747.9  998.67   757.6   999.4   786.7 1000.05
   806.4 1002.11   835.9 1006.35   894.9 1016.26   934.3 1021.65   963.8 1025.03
#Mann= 3 , 0 , 0
       0      .1       0   670.9    .045       0     703     .09       0
Bank Sta=670.9,703
XS Rating Curve= 0 ,0
Exp/Cntr=0.3,0.1

Type RM Length L Ch R = 1 ,10489.6 ,235,241.6,374.2
XS GIS Cut Line= 4
     1673444.376      745094.103     1673498.195      745168.755
     1673682.223      745333.686     1673767.292      745390.978
#Sta/Elev= 30
       0 1022.13    18.4 1018.24    27.6 1015.82    55.2 1006.32    64.4 1003.35
    73.6 1000.93    82.8   999.1      92  997.45   101.5  995.46   120.9  990.91
     130   989.3   139.6  988.86   177.6  989.69   196.6  990.27   206.1  990.83
   225.1   992.4   234.6  992.98   253.6  993.81   263.1  994.12   272.6  994.18
   291.6  994.04   301.1  994.22   310.6  994.75   320.1  995.95   329.6  997.96
   367.1    1008   376.4 1010.06   385.8 1011.38   413.7 1014.64   441.7 1018.22
#Mann= 3 , 0 , 0
       0      .1       0   120.9    .045       0   139.6      .1       0
Bank Sta=120.9,139.6
XS Rating Curve= 0 ,0
Exp/Cntr=0.3,0.1

Type RM Length L Ch R = 1 ,10248   ,114.5,121.9,131.4
XS GIS Cut Line= 4
     1673314.167      745250.353     1673366.251      745342.367
     1673541.598      745578.478     1673650.973      745630.561
#Sta/Elev= 30
       0 1019.82    38.4 1013.91    57.7 1011.27    76.9 1008.82    86.5 1006.92
    96.1 1002.99   105.7  997.28   115.5  992.24   125.3  989.82   135.1  988.81
   165.6  986.47   174.4  986.11     194  986.05   213.6  986.33   233.2  987.11
     243  987.66   282.2  990.26   331.2  992.26     390  994.86   409.2  995.96
   418.5  996.71   427.8   997.8   437.1  999.63   455.7 1004.11   465.1 1006.53
   474.4 1009.14     493 1013.51   502.3 1015.34   511.7 1016.61     521 1017.61
#Mann= 3 , 0 , 0
       0      .1       0   165.6    .045       0     194      .1       0
Bank Sta=165.6,194
XS Rating Curve= 0 ,0
Exp/Cntr=0.3,0.1

Type RM Length L Ch R = 1 ,10126.1 ,67.2,74.7,80.1
XS GIS Cut Line= 4
     1673277.709      745330.214     1673300.278      745401.394
     1673364.515      745667.019     1673400.973      745779.867
#Sta/Elev= 30
       0 1012.57    18.7 1010.75    37.3 1009.18    46.7 1008.53    65.3 1007.74
    74.7 1004.05    84.4  996.54    94.2  990.86     104  988.76   113.7  987.99
   123.5   987.4   147.2  986.16   162.5  985.64   172.3   985.7   191.8  986.54
   221.1  988.22   250.4  990.59   260.1   991.1   269.9  991.39   289.4  991.59
   328.4   991.5   338.2   991.6     348  991.87   366.2  992.66   384.4  993.81
   402.7  995.25   430.1  997.66   439.2  998.99   448.3 1000.98   466.6 1005.52
#Mann= 3 , 0 , 0
       0      .1       0   147.2    .045       0   172.3      .1       0
Bank Sta=147.2,172.3
XS Rating Curve= 0 ,0
Exp/Cntr=0.3,0.1

Type RM Length L Ch R = 1 ,10051.4 ,43.4,41.5,41.5
XS GIS Cut Line= 2
     1673262.084      745321.533     1673253.403      745795.492
#Sta/Elev= 30
       0 1013.75      29 1010.87    48.4 1009.31      58 1008.75    67.7 1008.83
    77.4 1008.63    87.1  1004.6    96.7  996.94   106.4  991.02   116.1  988.78
   125.8  987.99   164.5  985.55   183.8  985.11   193.5   985.1   203.2  985.14
   208.6  985.38   212.8  985.56   232.2  987.96   241.9  988.86   261.2  989.88
   309.6  990.96     358  990.68   367.6  990.95   377.3  991.93   396.6   994.4
   406.3  995.85     416  997.69   425.7  999.83     445 1004.72     474 1013.13
#Mann= 3 , 0 , 0
       0      .1       0   183.8    .045       0   208.6      .1       0
Bank Sta=183.8,208.6
XS Rating Curve= 0 ,0
Exp/Cntr=0.3,0.1

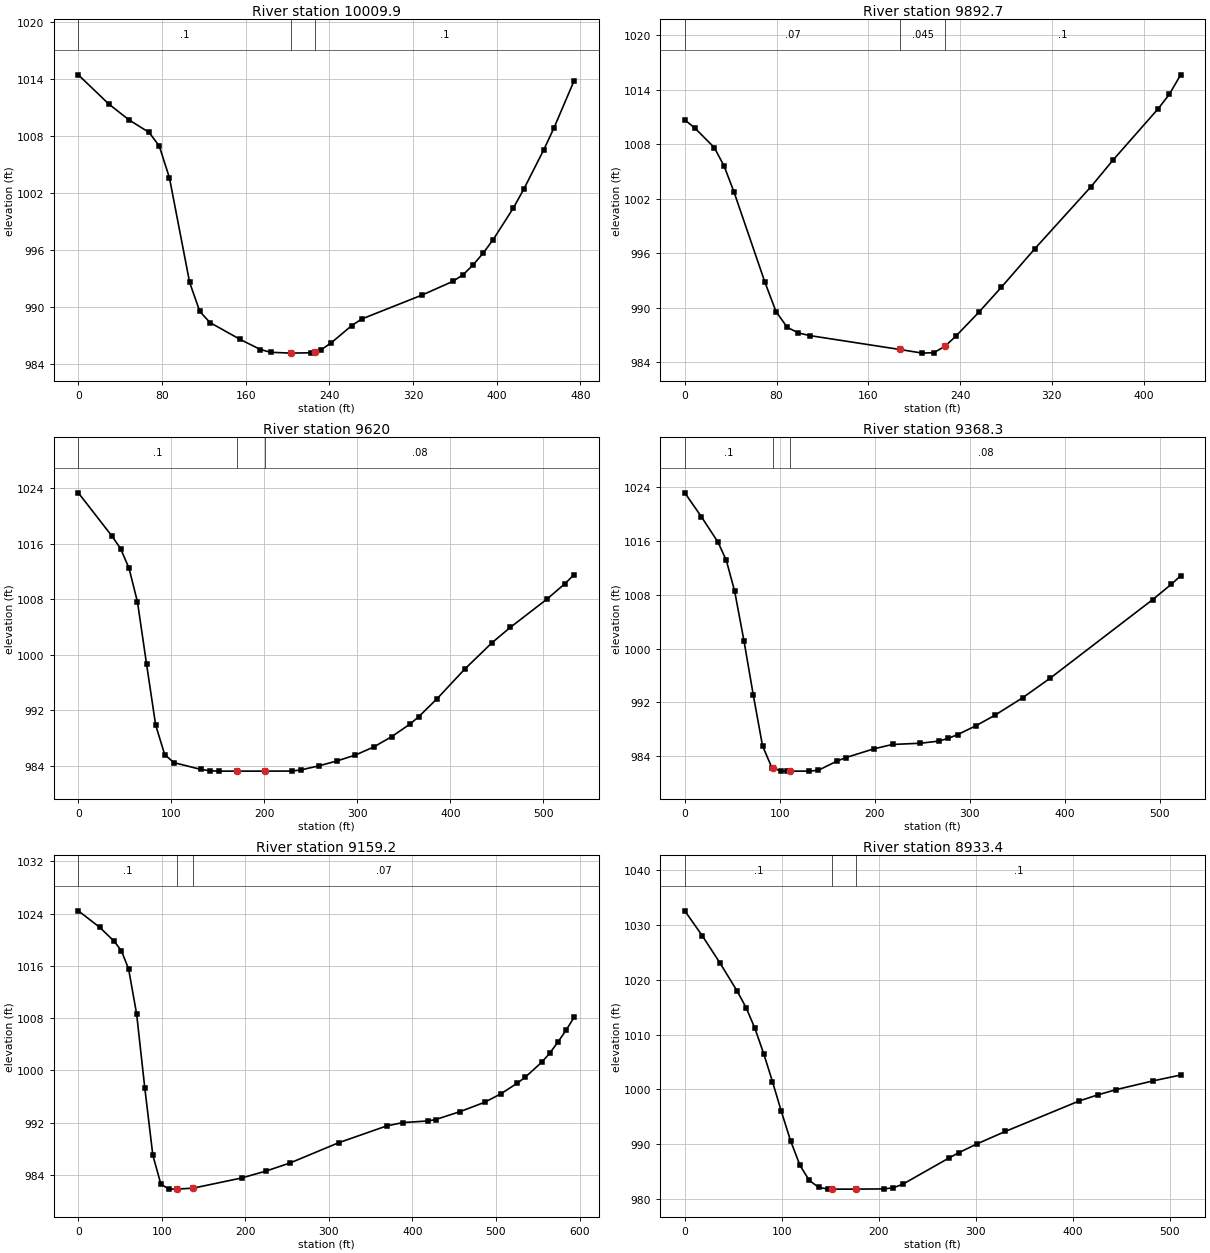
Type RM Length L Ch R = 1 ,10009.9 ,109.1,117.1,125.1
XS GIS Cut Line= 2
     1673222.153      745314.589     1673213.473      745788.547
#Sta/Elev= 30
       0 1014.46      29 1011.39    48.4 1009.71    67.7 1008.38    77.4 1006.94
    87.1 1003.59   106.4  992.56   116.1   989.5   125.8  988.33   154.8  986.54
   174.1  985.48   183.8  985.19   203.2   985.1   222.5  985.14   225.8  985.25
   232.2  985.46   241.9   986.2   261.2  987.99   270.9   988.7   328.9  991.24
     358  992.67   367.6  993.35   377.3  994.39     387  995.65   396.6  997.08
     416 1000.43   425.7 1002.37     445 1006.56   454.7 1008.86     474 1013.85
#Mann= 3 , 0 , 0
       0      .1       0   203.2    .045       0   225.8      .1       0
Bank Sta=203.2,225.8
XS Rating Curve= 0 ,0
Exp/Cntr=0.3,0.1

Type RM Length L Ch R = 1 ,9892.7  ,270,272.8,273.6
XS GIS Cut Line= 4
     1673185.695      745342.367     1673156.181       745394.45
     1673078.056      745595.839      1673045.07      745748.617
#Sta/Elev= 23
       0 1010.66     8.6 1009.79    25.7 1007.62    34.2  1005.6    42.8 1002.76
    69.7  992.84    79.5  989.56    89.3  987.82    99.1   987.2     109  986.91
   187.5  985.38   207.1  984.98     217  985.03   226.8  985.73   236.6  986.89
   256.2  989.47   275.9  992.23   305.2  996.49     354  1003.3   373.6 1006.29
   412.6 1011.89   422.4 1013.49   432.2 1015.63
#Mann= 3 , 0 , 0
       0     .07       0   187.5    .045       0   226.8      .1       0
Bank Sta=187.5,226.8
XS Rating Curve= 0 ,0
Exp/Cntr=0.3,0.1

Type RM Length L Ch R = 1 ,9620    ,250.8,251.7,254
XS GIS Cut Line= 4
     1672994.723      745205.214     1672958.265      745257.297
     1672808.959      745531.603     1672765.556      745682.644
#Sta/Elev= 30
       0 1023.37    36.3  1017.1    45.4 1015.32    54.5 1012.48    63.6  1007.6
    73.3  998.68    83.1  989.87    92.8   985.6   102.6  984.43   131.9  983.44
   141.6  983.25   151.4   983.2   170.9   983.2   200.2   983.2   229.5  983.21
   239.2  983.37   258.8  983.97   278.3  984.68   297.8  985.52   317.3  986.67
   336.8  988.17   356.4  989.98   366.1  991.08   385.7  993.66   415.2   997.9
   444.6 1001.72   464.3 1003.94   503.6 1008.01   523.2 1010.27     533 1011.57
#Mann= 3 , 0 , 0
       0      .1       0   170.9    .045       0   200.2     .08       0
Bank Sta=170.9,200.2
XS Rating Curve= 0 ,0
Exp/Cntr=0.3,0.1

Type RM Length L Ch R = 1 ,9368.3  ,209.5,209.1,208.6
XS GIS Cut Line= 4
      1672755.14      745137.505     1672725.626      745180.908
     1672581.528      745436.117     1672564.167      745611.464
#Sta/Elev= 30
       0 1023.12    17.5 1019.56      35 1015.78    43.7 1013.09    52.5 1008.49
    62.3 1001.12      72  993.16    81.8  985.56    91.6  982.32    92.7  982.26
   101.3  981.81   107.7   981.8   111.1   981.8   130.6   981.8   140.4  981.92
     160  983.28   169.7  983.82     199  985.11   218.6  985.76   247.9  985.94
   267.4  986.26   277.2  986.67     287  987.21   306.5  988.55     326  990.07
   355.4  992.68   384.7  995.62   492.4 1007.27     512 1009.54   521.8  1010.8
#Mann= 3 , 0 , 0
       0      .1       0    92.7    .045       0   111.1     .08       0
Bank Sta=92.7,111.1
XS Rating Curve= 0 ,0
Exp/Cntr=0.3,0.1

Type RM Length L Ch R = 1 ,9159.2  ,225.3,225.9,226.3
XS GIS Cut Line= 4
     1672590.209      745087.158     1672546.806      745128.825
      1672388.82      745417.019     1672362.778      745620.144
#Sta/Elev= 30
       0 1024.44    25.8 1021.89      43 1019.76    51.6 1018.31    60.2 1015.52
    69.8 1008.62    79.5  997.37    89.2  986.99    98.8  982.57   108.5   981.8
   118.2  981.81   137.5  981.95   195.5  983.51   224.5  984.56   253.5  985.81
   311.5   988.9   369.5   991.5   388.8     992   418.1  992.24   427.8  992.46
   457.1  993.68   486.3   995.1   505.8   996.4   525.4  998.02   535.1  998.96
   554.6 1001.22   564.4 1002.63   574.1 1004.32   583.9 1006.14   593.6 1008.14
#Mann= 3 , 0 , 0
       0      .1       0   118.2    .045       0   137.5     .07       0
Bank Sta=118.2,137.5
XS Rating Curve= 0 ,0
Exp/Cntr=0.3,0.1

Type RM Length L Ch R = 1 ,8933.4  ,271.6,272.8,273.8
XS GIS Cut Line= 4
     1672361.042      744981.255     1672340.209      745078.478
     1672230.834      745271.186      1672130.14      745432.644
#Sta/Elev= 28
       0 1032.61    18.1 1028.04    36.2 1023.11    54.2  1017.9    63.3  1014.9
    72.3 1011.15    81.4 1006.52    90.4 1001.44    99.4  996.07   109.1  990.62
   118.7  986.17   128.3   983.4     138  982.14   147.6   981.8     152   981.8
   176.5   981.8   205.4  981.84     215  982.04   224.7  982.69   272.8  987.52
   282.5  988.45   301.7  990.09   330.5  992.33   406.6  997.89   425.7     999
   444.7  999.96   482.8 1001.56   511.3 1002.63
#Mann= 3 , 0 , 0
       0      .1       0     152    .045       0   176.5      .1       0
Bank Sta=152,176.5
XS Rating Curve= 0 ,0
Exp/Cntr=0.3,0.1

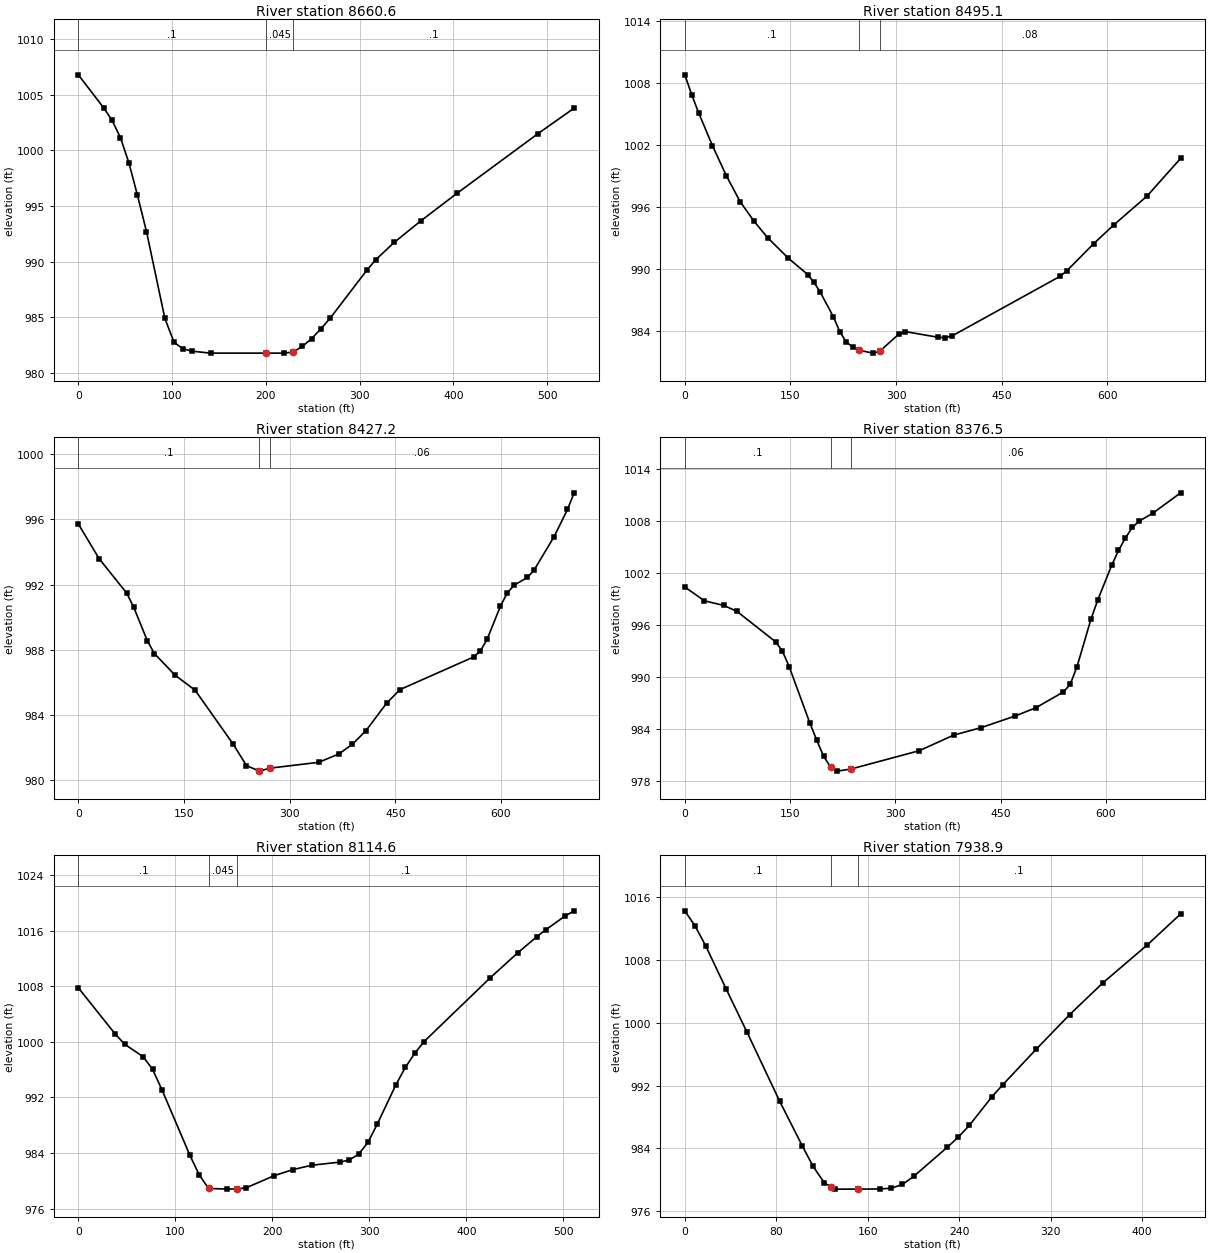
Type RM Length L Ch R = 1 ,8660.6  ,159.9,165.6,171.1
XS GIS Cut Line= 4
     1672180.487      744936.117     1672131.876      744976.047
     1671984.306       745206.95     1671965.209      745397.922
#Sta/Elev= 26
       0 1006.79      27 1003.83      36  1002.7    44.9 1001.15    53.9   998.9
    62.9  996.03    72.7  992.72    92.3  984.92   102.1  982.77   111.8  982.18
   121.6  981.97   141.2   981.8   199.9   981.8   219.5   981.8   229.3   981.9
   239.1  982.41   248.9  983.11   258.6  983.97   268.4  984.91   307.6  989.23
   317.4   990.2   336.9  991.74   365.7   993.7   404.1  996.16   490.5 1001.52
   528.9  1003.8
#Mann= 3 , 0 , 0
       0      .1       0   199.9    .045       0   229.3      .1       0
Bank Sta=199.9,229.3
XS Rating Curve= 0 ,0
Exp/Cntr=0.3,0.1

Type RM Length L Ch R = 1 ,8495.1  ,67.8,67.8,67.9
XS GIS Cut Line= 6
      1672201.32      744783.339     1672078.056      744880.561
     1672048.542      744899.658     1671937.431      745012.505
     1671885.348      745094.103     1671835.001      745345.839
#Sta/Elev= 30
       0 1008.77     9.8 1006.85    19.6  1005.1    39.2 1001.92    58.9  999.01
    78.5   996.5    98.1  994.61   117.7  992.99   147.2     991   174.6  989.43
   183.4  988.67   192.1  987.75   210.8  985.36   220.1  983.89   229.4  982.89
   238.7   982.4     248   982.1   266.7  981.82   276.6  981.99   303.9  983.66
   313.2   983.9   360.2  983.35   369.9  983.33   379.6  983.49   532.9  989.26
   542.4  989.79   580.4  992.41     609  994.23   656.5  997.04     704 1000.68
#Mann= 3 , 0 , 0
       0      .1       0     248    .045       0   276.6     .08       0
Bank Sta=248,276.6
XS Rating Curve= 0 ,0
Exp/Cntr=0.3,0.1

Type RM Length L Ch R = 1 ,8427.2  ,53.5,50.7,47.9
XS GIS Cut Line= 6
     1672159.653      744731.255      1672036.39      744828.478
     1672006.876      744847.575     1671895.765      744960.422
     1671843.681      745042.019     1671793.334      745293.755
#Sta/Elev= 30
       0  995.72    29.4   993.6    68.7  991.48    78.5  990.63    98.1  988.55
   107.9  987.78   137.4  986.45   165.8  985.53   220.1  982.21   238.7  980.91
   256.6  980.58   257.4  980.57   271.6  980.75   341.2  981.11   369.9  981.62
   389.2  982.22   408.6  983.06   437.6  984.73   456.8  985.57   561.4  987.57
   570.9  987.94   580.4  988.65   599.4  990.69     609  991.49   618.5  991.96
   637.5  992.44     647  992.89   675.5  994.94   694.5  996.61     704  997.63
#Mann= 3 , 0 , 0
       0      .1       0   256.6    .045       0   271.6     .06       0
Bank Sta=256.6,271.6
XS Rating Curve= 0 ,0
Exp/Cntr=0.3,0.1

Type RM Length L Ch R = 1 ,8376.5  ,258,261.9,267.1
XS GIS Cut Line= 4
     1671996.459      744668.755     1671965.209      744804.172
     1671710.001      745137.505     1671578.056      745203.478
#Sta/Elev= 30
       0 1000.39    27.8   998.8    55.6  998.26    74.1  997.59   129.7  994.05
     139     993   148.7  991.21     178  984.74   187.8  982.77   197.6  980.91
   207.9   979.6   217.1  979.17   236.6  979.41   334.2  981.53     383  983.32
   422.1  984.18   470.9  985.53   500.2  986.48   539.3  988.29     549  989.17
   558.8  991.22   578.5  996.66   588.3   998.9     608 1002.87   617.8  1004.6
   627.6 1006.02   637.5 1007.26   647.3 1007.98     667 1008.91   706.3 1011.24
#Mann= 3 , 0 , 0
       0      .1       0   207.9    .045       0   236.6     .06       0
Bank Sta=207.9,236.6
XS Rating Curve= 0 ,0
Exp/Cntr=0.3,0.1

Type RM Length L Ch R = 1 ,8114.6  ,180.6,175.7,169.1
XS GIS Cut Line= 4
     1671867.987      744576.742     1671803.751      744634.033
     1671612.778      744781.603     1671503.403      744929.172
#Sta/Elev= 30
       0  1007.8    38.2 1001.11    47.8  999.67      67  997.85    76.5  996.06
    86.1  993.14     115  983.67   124.7  980.83   134.3   978.9   153.6   978.8
   163.3  978.83     173  978.99   201.9  980.74   221.2  981.61   240.5  982.24
   269.5  982.69   279.2  982.99   288.8  983.82   298.5  985.52   308.1  988.15
   327.4  993.85   337.1  996.33   346.8  998.38   356.4 1000.06   424.1 1009.18
   453.1 1012.86   472.4 1015.14   482.1 1016.19   501.4 1018.11   511.1 1018.89
#Mann= 3 , 0 , 0
       0      .1       0   134.3    .045       0   163.3      .1       0
Bank Sta=134.3,163.3
XS Rating Curve= 0 ,0
Exp/Cntr=0.3,0.1

Type RM Length L Ch R = 1 ,7938.9  ,264.2,267.2,269.4
XS GIS Cut Line= 4
     1671706.528      744453.478      1671670.07      744505.561
     1671527.709      744691.325      1671473.89      744816.325
#Sta/Elev= 26
       0 1014.27     9.1 1012.31    18.2 1009.83    36.3 1004.27    54.5  998.78
    83.1  989.97   102.6  984.36   112.3  981.69   122.1  979.58   127.8  979.12
   131.8   978.8   151.3   978.8   170.8  978.82   180.6  978.92   190.4   979.4
   200.1  980.41   229.4  984.11   239.1  985.41   248.9  986.92   268.4  990.53
   278.1   992.1   307.3  996.62   336.5 1001.02   365.7 1005.09   404.6 1009.93
   433.7 1013.88
#Mann= 3 , 0 , 0
       0      .1       0   127.8    .045       0   151.3      .1       0
Bank Sta=127.8,151.3
XS Rating Curve= 0 ,0
Exp/Cntr=0.3,0.1

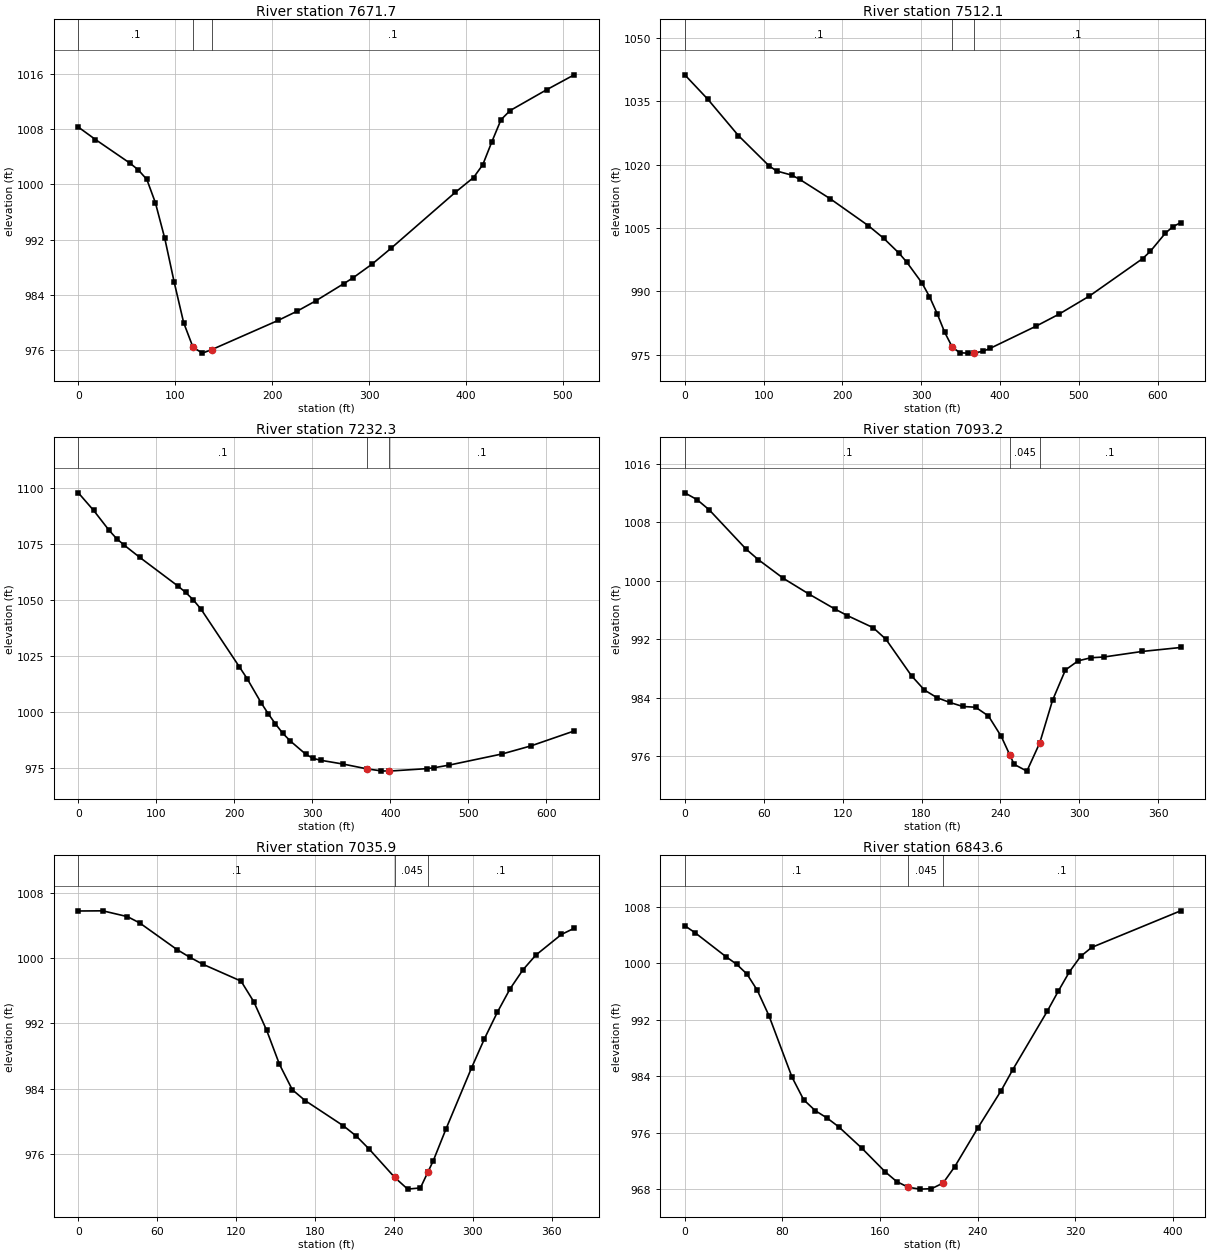
Type RM Length L Ch R = 1 ,7671.7  ,164.5,159.7,154.9
XS GIS Cut Line= 4
     1671552.015      744293.755     1671484.306      744335.422
     1671308.959      744517.714     1671215.209      744670.492
#Sta/Elev= 27
       0 1008.26    17.7 1006.46      53 1003.07    61.8 1002.08    70.7 1000.69
    79.5  997.33    89.2  992.17      99  985.79   108.7  979.97   118.4   976.4
   128.1  975.57   137.9  976.09     206  980.29   225.4  981.61   244.9  983.12
   274.1  985.63   283.8  986.49   303.2  988.45   322.7  990.73     389  998.82
   407.9 1000.97   417.4 1002.82   426.8 1006.15   436.2 1009.33   445.6 1010.65
   483.4 1013.67   511.7 1015.82
#Mann= 3 , 0 , 0
       0      .1       0   118.4    .045       0   137.9      .1       0
Bank Sta=118.4,137.9
XS Rating Curve= 0 ,0
Exp/Cntr=0.3,0.1

Type RM Length L Ch R = 1 ,7512.1  ,311.7,279.8,248.3
XS GIS Cut Line= 4
     1671585.102      744067.555     1671352.362      744226.047
     1671220.417      744439.589     1671190.903      744531.603
#Sta/Elev= 30
       0  1041.3    29.1 1035.54      68 1026.92   106.8 1019.77   116.5 1018.53
   135.9 1017.54   145.6 1016.57   184.5 1011.96     233 1005.57   252.4 1002.59
   271.9  999.06   281.6  996.96   300.9  992.03   310.5  988.79   320.2  984.77
   329.8  980.33   339.5  976.79   349.2  975.48   358.8   975.4   366.8  975.45
   378.1  975.81   387.8  976.56   445.7  981.78   474.7  984.61   513.3   988.9
   580.9  997.77   590.6  999.47   609.9 1003.82   619.6 1005.37   629.2 1006.28
#Mann= 3 , 0 , 0
       0      .1       0   339.5    .045       0   366.8      .1       0
Bank Sta=339.5,366.8
XS Rating Curve= 0 ,0
Exp/Cntr=0.3,0.1

Type RM Length L Ch R = 1 ,7232.3  ,144.7,139.1,132.2
XS GIS Cut Line= 5
     1670853.765      743922.155      1670943.06      744119.265
     1670970.417      744142.714     1671185.695      744338.894
     1671190.903      744430.908
#Sta/Elev= 30
       0 1097.83    19.7 1089.96    39.3 1081.18    49.2 1077.36      59 1074.46
    78.7 1069.07   127.9 1056.23   137.7 1053.41   147.5 1050.07   157.4 1045.93
   206.6  1020.2   216.4 1015.02   234.4 1004.22   243.4   999.4   252.4  994.98
   262.1  990.65   271.8   987.2   291.3  981.39     301  979.44   310.7  978.61
   339.8  976.89   369.8  974.79   388.3  973.87     398  973.76   446.6  974.86
   456.3  975.27   475.7  976.46   543.7  981.44   580.6  985.03   635.8  991.66
#Mann= 3 , 0 , 0
       0      .1       0   369.8    .045       0     398      .1       0
Bank Sta=369.8,398
XS Rating Curve= 0 ,0
Exp/Cntr=0.3,0.1

Type RM Length L Ch R = 1 ,7093.2  ,57.3,57.3,57.3
XS GIS Cut Line= 3
     1670831.528      744231.255     1670890.556      744259.033
      1671161.39      744413.547
#Sta/Elev= 30
       0 1012.01     9.3 1011.08    18.6 1009.68    46.6 1004.32    55.9 1002.88
      75 1000.32    94.5  998.17     114  996.15   123.7  995.23   143.2  993.59
   152.9  992.01   172.4  987.01   182.2  985.07   191.9  984.01   201.6  983.37
   211.4  982.82   221.1  982.72   230.9  981.52   240.6  978.74   247.2  976.17
   250.4  974.92   260.1  973.99   269.9  977.85   279.6  983.66   289.4  987.81
   299.1  989.06   308.8  989.48   318.6  989.58   347.8  990.34     377  990.88
#Mann= 3 , 0 , 0
       0      .1       0   247.2    .045       0   269.9      .1       0
Bank Sta=247.2,269.9
XS Rating Curve= 0 ,0
Exp/Cntr=0.3,0.1

Type RM Length L Ch R = 1 ,7035.9  ,176.2,192.3,208.6
XS GIS Cut Line= 3
     1670808.959      744283.339     1670867.987      744311.117
      1671138.82       744465.63
#Sta/Elev= 30
       0 1005.78    18.6  1005.8    37.3 1005.09    46.6 1004.32      75 1001.05
    84.7 1000.11    94.5  999.26   123.7  997.18   133.4  994.65   143.2  991.14
   152.9  986.98   162.7  983.85   172.4  982.53   201.6  979.42   211.4  978.16
   221.1  976.58   240.6  973.09   250.4  971.66   260.1  971.81     266  973.82
   269.9  975.15   279.6  979.06   299.1  986.58   308.8  990.11   318.6  993.36
   328.3  996.24   338.1  998.57   347.8 1000.36   367.3  1002.9     377 1003.66
#Mann= 3 , 0 , 0
       0      .1       0   240.6    .045       0     266      .1       0
Bank Sta=240.6,266
XS Rating Curve= 0 ,0
Exp/Cntr=0.3,0.1

Type RM Length L Ch R = 1 ,6843.6  ,216.7,236.9,257.1
XS GIS Cut Line= 4
     1670831.528      744328.478     1670847.153      744385.769
     1670918.334      744602.783     1670927.015      744720.839
#Sta/Elev= 29
       0  1005.3     8.5  1004.3    33.9  1000.9    42.4  999.86    50.9  998.47
    59.4  996.16    68.9  992.59    87.9  983.85    97.4  980.67     107  979.12
   116.5   978.1     126  976.86     145  973.83   164.1  970.49   173.6   969.1
   183.1  968.29   192.6  968.03   202.1  968.09   211.6  968.89   221.2  971.22
   240.2  976.72   259.2  981.98   268.7  984.94   296.9  993.19     306  996.05
   315.1  998.78   324.2 1000.95   333.3 1002.23   406.2 1007.41
#Mann= 3 , 0 , 0
       0      .1       0   183.1    .045       0   211.6      .1       0
Bank Sta=183.1,211.6
XS Rating Curve= 0 ,0
Exp/Cntr=0.3,0.1

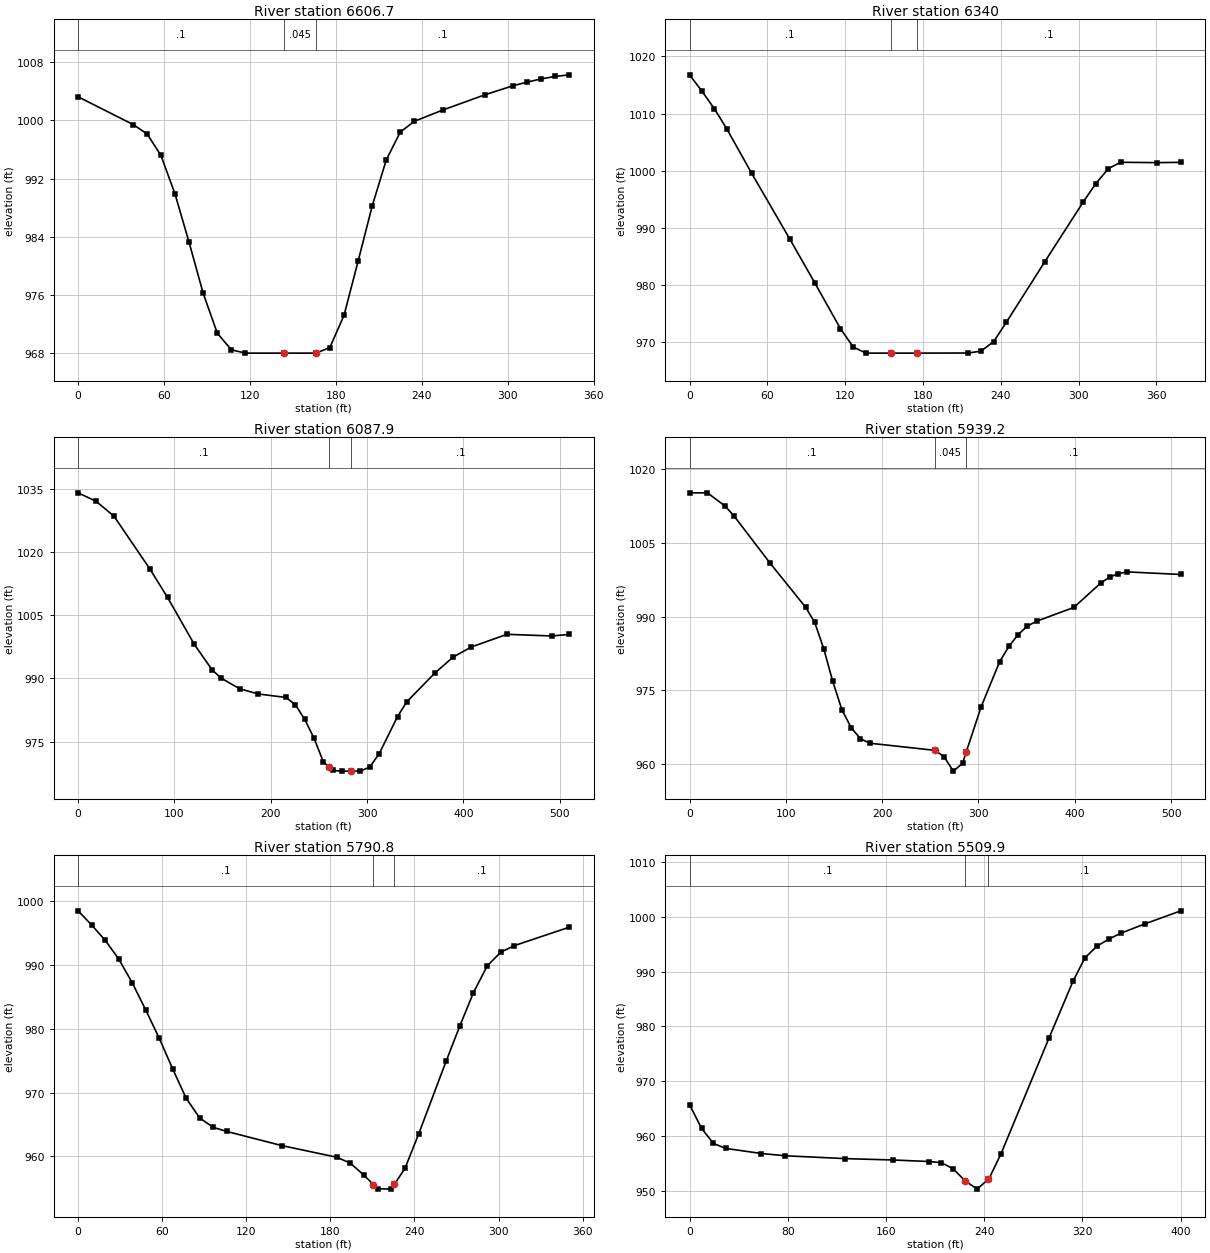
Type RM Length L Ch R = 1 ,6606.7  ,278.5,266.7,254.8
XS GIS Cut Line= 3
     1670762.084      744302.436      1670723.89      744345.839
     1670574.584      744588.894
#Sta/Elev= 26
       0 1003.23    38.5  999.41    48.2  998.12    57.8  995.19    67.6  989.92
    77.5  983.23    87.3  976.25    97.2  970.74     107  968.46   116.8     968
   143.6     968     166     968   175.8  968.76   185.7   973.2   195.5  980.61
   205.4  988.24   215.2  994.55     225  998.39   234.9  999.87   254.5  1001.4
     284  1003.5   303.7 1004.75   313.6 1005.25   323.4 1005.69   333.2 1006.03
   343.1 1006.25
#Mann= 3 , 0 , 0
       0      .1       0   143.6    .045       0     166      .1       0
Bank Sta=143.6,166
XS Rating Curve= 0 ,0
Exp/Cntr=0.3,0.1

Type RM Length L Ch R = 1 ,6340    ,272.5,252,231.2
XS GIS Cut Line= 4
     1670470.417      744118.408     1670466.945        744175.7
     1670460.001      744441.325     1670465.209       744496.88
#Sta/Elev= 23
       0 1016.78     9.6  1013.9    19.1 1010.85    28.7 1007.32    47.8  999.56
    77.1  988.08    96.8  980.23   116.4  972.28   126.3  969.06   136.1     968
   155.1     968   175.5     968   214.9  968.02   224.7  968.35   234.5     970
   244.4  973.44   273.9  983.99   303.4  994.42   313.3  997.71   323.1 1000.36
   332.4 1001.45   360.3 1001.39   378.9 1001.44
#Mann= 3 , 0 , 0
       0      .1       0   155.1    .045       0   175.5      .1       0
Bank Sta=155.1,175.5
XS Rating Curve= 0 ,0
Exp/Cntr=0.3,0.1

Type RM Length L Ch R = 1 ,6087.9  ,148.6,148.7,148.6
XS GIS Cut Line= 4
     1670046.806      744189.589     1670149.237      744297.228
     1670343.681      744455.214     1670444.376      744502.089
#Sta/Elev= 30
       0 1034.01    18.6 1032.01    37.2 1028.49    74.3 1016.03    92.9 1009.19
   120.7  998.05   139.3  991.98   148.6  990.05   167.9  987.52   187.1   986.3
     216  985.47   225.7  983.73   235.3  980.27     245  975.81   254.6  970.23
   260.5  968.95   264.2  968.15   273.9     968   283.5     968   293.1     968
   302.8  968.97   312.4  972.02   331.7  980.94   341.3  984.44   370.2  991.21
   389.5  995.06   408.4  997.45   445.4 1000.45   491.7 1000.06   510.2 1000.42
#Mann= 3 , 0 , 0
       0      .1       0   260.5    .045       0   283.5      .1       0
Bank Sta=260.5,283.5
XS Rating Curve= 0 ,0
Exp/Cntr=0.3,0.1

Type RM Length L Ch R = 1 ,5939.2  ,145.9,148.4,150.8
XS GIS Cut Line= 4
     1669932.223      744286.811     1670034.653       744394.45
     1670229.098      744552.436     1670329.792      744599.311
#Sta/Elev= 30
       0 1015.23    18.6 1015.24    37.2  1012.5    46.4 1010.47    83.6 1000.92
   120.7  991.88     130  988.83   139.3   983.5   148.6   976.9   158.2  971.04
   167.9  967.36   177.5  965.14   187.1  964.22   254.6  962.77   264.2   961.5
   273.9  958.53   283.5  960.12   287.2  962.36   302.8  971.63     322  980.82
   331.7  983.97   341.3  986.37   350.9   988.1   360.6  989.09   399.1  991.89
   426.9  996.84   436.2  998.07   445.4  998.78   454.7  999.13   510.2   998.6
#Mann= 3 , 0 , 0
       0      .1       0   254.6    .045       0   287.2      .1       0
Bank Sta=254.6,287.2
XS Rating Curve= 0 ,0
Exp/Cntr=0.3,0.1

Type RM Length L Ch R = 1 ,5790.8  ,279.7,280.9,282
XS GIS Cut Line= 3
     1669896.633       744394.45     1669934.827      744482.992
     1670113.646      744663.547
#Sta/Elev= 29
       0  998.49     9.6  996.28    19.3  993.88    28.9  990.96    38.6  987.22
    48.2  982.97    57.9  978.51    67.5   973.7    77.1   969.1    86.8     966
    96.4  964.54   106.2  963.89   145.3  961.68   184.4  959.86   194.2  958.94
   203.9  957.05   210.7  955.57   213.7  954.92   223.5  954.85   225.7  955.59
   233.3  958.13     243  963.48   262.6   974.9   272.4  980.44   282.1  985.65
   291.9  989.84   301.7  992.02   311.4  993.04   350.6  995.93
#Mann= 3 , 0 , 0
       0      .1       0   210.7    .045       0   225.7      .1       0
Bank Sta=210.7,225.7
XS Rating Curve= 0 ,0
Exp/Cntr=0.3,0.1

Type RM Length L Ch R = 1 ,5509.9  ,345.2,345.6,344.5
XS GIS Cut Line= 2
     1669640.006      744563.865     1669906.934      744862.043
#Sta/Elev= 24
       0  965.71     9.8  961.38    19.5  958.63    29.3  957.73    58.6  956.79
    78.1  956.38   126.9  955.86   165.9  955.61   195.2  955.33     205  955.13
   214.7     954   224.5   951.8   234.3  950.29   243.4  952.11     244  952.23
   253.8  956.79   292.8  977.87   312.4  988.27   322.1  992.53   331.9  994.65
   341.6  995.95   351.4  997.02   370.9  998.72   400.2  1001.1
#Mann= 3 , 0 , 0
       0      .1       0   224.5    .045       0   243.4      .1       0
Bank Sta=224.5,243.4
XS Rating Curve= 0 ,0
Exp/Cntr=0.3,0.1