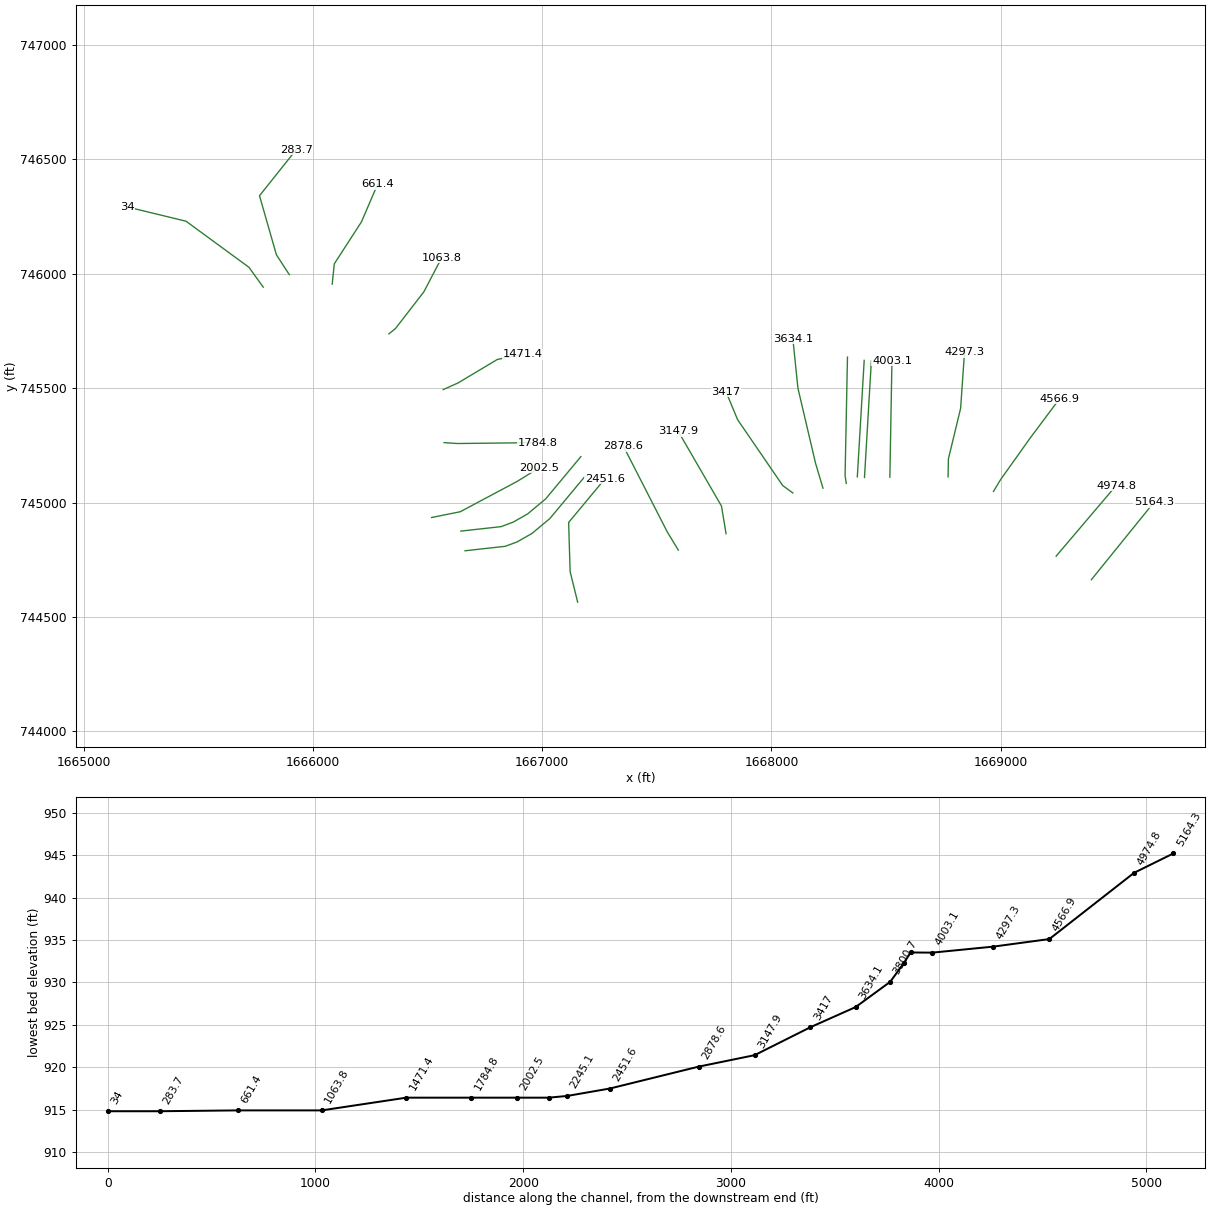
HEC-RAS study SFTOMLINRN.prj: SFTOMLINRN

--- SFTOMLINRN.g01 (geometry) --- (continued)

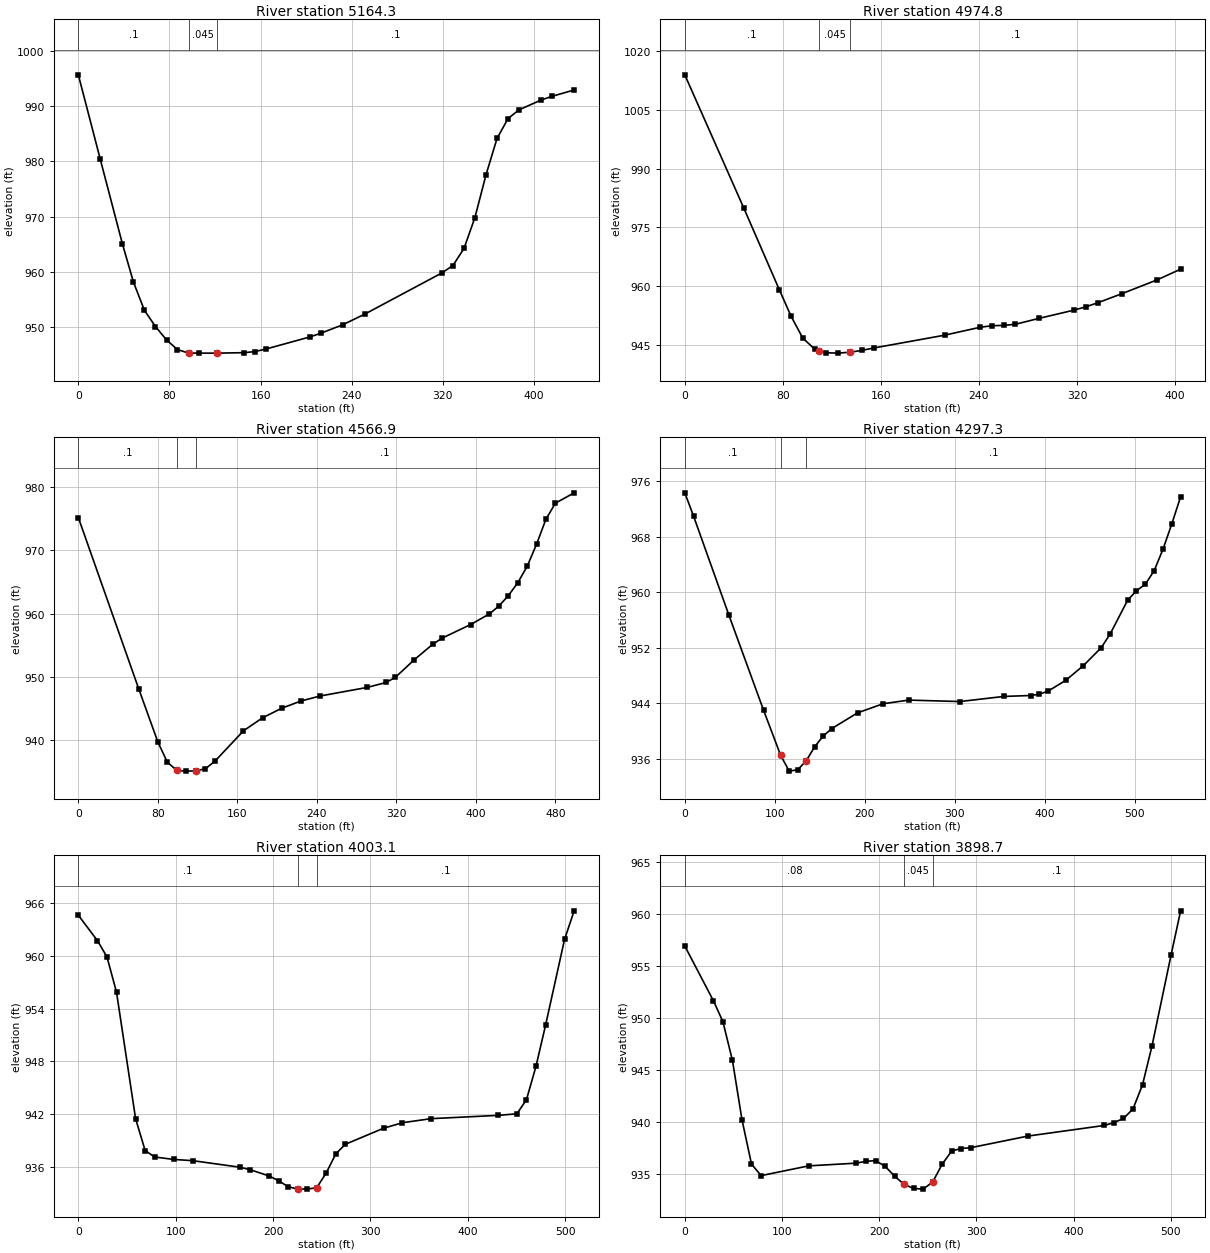
Type RM Length L Ch R = 1 ,5164.3  ,188.8,189.6,191.1
XS GIS Cut Line= 2
     1669395.215      744662.824     1669668.652      745001.365
#Sta/Elev= 29
       0  995.73    19.3  980.36    38.7  965.03    48.4  958.09      58  952.97
    67.7  950.03    77.4   947.6      87  945.84    96.7  945.22   106.3   945.2
   121.3   945.2   145.1  945.28   154.7  945.47   164.4  945.93   203.1  948.13
   212.8  948.81   232.1  950.35   251.4  952.28   319.1  959.76   328.8  961.11
   338.5   964.2   348.1  969.82   357.8  977.56   367.5  984.18   377.2   987.8
   386.8  989.37   406.2  991.16   415.8  991.83   435.2  992.98
#Mann= 3 , 0 , 0
       0      .1       0    96.7    .045       0   121.3      .1       0
Bank Sta=96.7,121.3
XS Rating Curve= 0 ,0
Exp/Cntr=0.3,0.1

Type RM Length L Ch R = 1 ,4974.8  ,405.7,407.9,409.4
XS GIS Cut Line= 2
     1669241.569      744765.688     1669503.288      745074.282
#Sta/Elev= 24
       0 1013.95    48.2   979.9    77.1  959.12    86.7  952.34    96.3  946.74
     106  943.93   109.9  943.55   115.6     943   124.9  942.91   134.9  943.14
   144.5  943.61   154.2  944.22     212  947.49   240.8   949.5   250.5   949.9
   260.1  949.99   269.8  950.28     289  951.78   317.9  953.91   327.6  954.77
   337.2  955.79   356.5  958.06   385.4  961.61   404.6  964.34
#Mann= 3 , 0 , 0
       0      .1       0   109.9    .045       0   134.9      .1       0
Bank Sta=109.9,134.9
XS Rating Curve= 0 ,0
Exp/Cntr=0.3,0.1

Type RM Length L Ch R = 1 ,4566.9  ,261.1,269.5,278.2
XS GIS Cut Line= 4
     1668968.131       745048.24     1668999.381      745100.324
     1669126.986      745280.011     1669257.194       745454.49
#Sta/Elev= 30
       0  975.21    60.7  948.14    79.9  939.76    89.5  936.52    99.1  935.21
   108.6   935.1   118.2  935.14   127.8  935.47   137.4  936.67   166.1  941.47
   185.3  943.53   204.5  945.04   223.6  946.17   242.8  946.97   290.6  948.34
   309.5  949.12     319  949.94   337.9  952.71   356.8   955.2   366.3  956.16
   394.7  958.29   413.6  959.97   423.1  961.22   432.6  962.86     442  964.88
   451.5  967.48     461     971   470.4  974.94   479.9  977.48   498.8  979.12
#Mann= 3 , 0 , 0
       0      .1       0    99.1    .045       0   118.2      .1       0
Bank Sta=99.1,118.2
XS Rating Curve= 0 ,0
Exp/Cntr=0.3,0.1

Type RM Length L Ch R = 1 ,4297.3  ,286.1,294.3,299.9
XS GIS Cut Line= 4
     1668770.215      745112.043     1668771.517      745190.168
     1668824.902      745411.522     1668841.829      745656.313
#Sta/Elev= 30
       0  974.33     9.8  970.95    48.8  956.78    87.6  942.98   106.6  936.47
   116.1  934.21   125.6  934.41   135.1  935.73   144.6  937.76     154  939.29
   163.5  940.35     192  942.61   220.4  943.92   248.9  944.45   305.8  944.24
   354.9  944.98   384.4  945.11   394.2   945.3     404  945.75   423.6  947.31
   443.2  949.43   462.9     952   472.7  953.94   492.3  958.85   502.1  960.21
     512  961.16   521.8  963.11   531.6   966.2   541.4  969.85   551.2  973.77
#Mann= 3 , 0 , 0
       0      .1       0   106.6    .045       0   135.1      .1       0
Bank Sta=106.6,135.1
XS Rating Curve= 0 ,0
Exp/Cntr=0.3,0.1

Type RM Length L Ch R = 1 ,4003.1  ,108.1,104.4,103
XS GIS Cut Line= 2
     1668516.309       745110.74     1668525.423      745619.855
#Sta/Elev= 30
       0  964.59    19.6  961.71    29.4  959.86    39.2  955.86    58.8   941.5
    68.6  937.88    78.3  937.15    97.9  936.87   117.5  936.73   166.5  935.98
   176.3  935.71   195.8     935   205.6  934.46   215.4  933.77   225.2  933.52
     235   933.5   244.8  933.66   254.6  935.34   264.4   937.5   274.2  938.59
   313.4  940.41   332.9  941.04   362.3   941.5   430.9  941.87   450.4  942.05
   460.2  943.65     470  947.44   479.8  952.09   499.4  961.88   509.2  965.09
#Mann= 3 , 0 , 0
       0      .1       0   225.2    .045       0   244.8      .1       0
Bank Sta=225.2,244.8
XS Rating Curve= 0 ,0
Exp/Cntr=0.3,0.1

Type RM Length L Ch R = 1 ,3898.7  ,31.8,31.6,31.8
XS GIS Cut Line= 2
     1668405.631      745109.438     1668435.579      745618.553
#Sta/Elev= 30
       0  956.92    29.4  951.66    39.2  949.64      49  945.91    58.8  940.21
    68.6  935.93    78.5  934.82   127.5  935.76   176.5  936.02   186.3   936.2
   196.2  936.26     206  935.72   215.8  934.77   225.6  933.97   235.4  933.59
   245.2  933.52     255  934.21   264.8  935.93   274.6   937.2   284.4  937.43
   294.2  937.51   353.1  938.63   431.5  939.65   441.3  939.92   451.2  940.32
     461  941.24   470.8  943.56   480.6  947.32   500.2  956.07     510  960.31
#Mann= 3 , 0 , 0
       0     .08       0   225.6    .045       0     255      .1       0
Bank Sta=225.6,255
XS Rating Curve= 0 ,0
Exp/Cntr=0.3,0.1

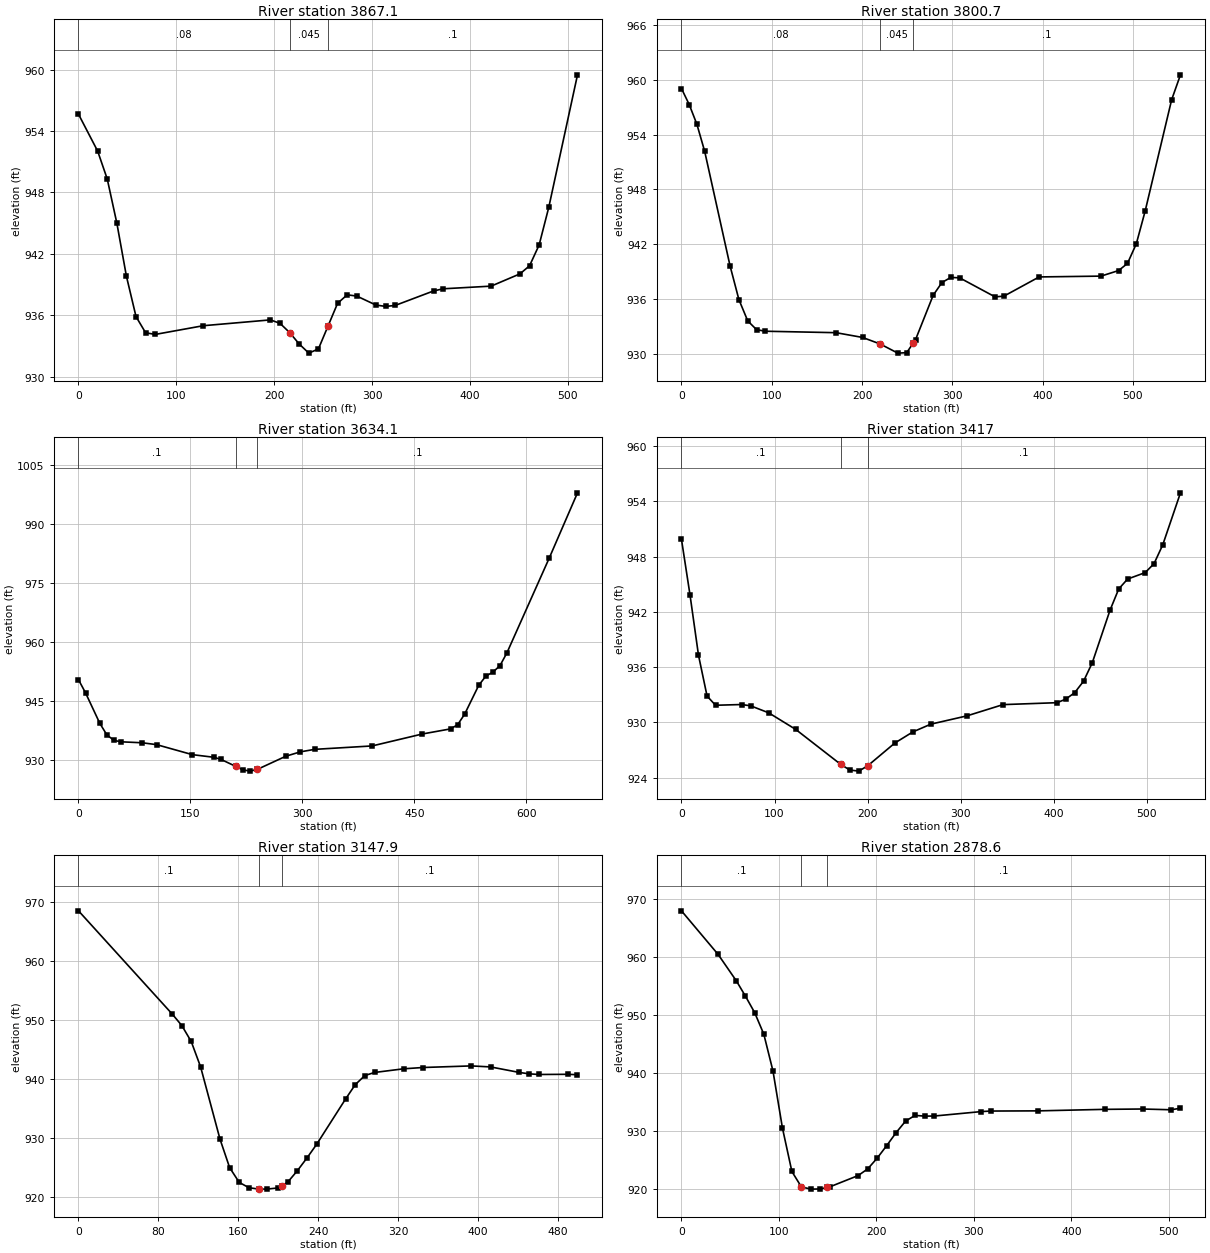
Type RM Length L Ch R = 1 ,3867.1  ,65.1,66.3,66.2
XS GIS Cut Line= 2
     1668374.381      745112.043     1668404.329      745621.157
#Sta/Elev= 30
       0  955.65    19.6  952.04    29.4  949.31    39.2     945      49   939.8
    58.8  935.86    68.6  934.28    78.5  934.12   127.5  934.97   196.2  935.54
     206   935.2   215.8   934.3   225.6  933.18   235.4  932.29   245.2   932.7
     255  934.93   264.8  937.16   274.6  937.99   284.4  937.87     304  936.99
   313.8  936.86   323.6  936.95   362.9  938.37   372.7  938.58   421.7  938.84
   451.2  940.04     461  940.83   470.8  942.87   480.6  946.53     510   959.5
#Mann= 3 , 0 , 0
       0     .08       0   215.8    .045       0     255      .1       0
Bank Sta=215.8,255
XS Rating Curve= 0 ,0
Exp/Cntr=0.3,0.1

Type RM Length L Ch R = 1 ,3800.7  ,160.8,166.6,172.8
XS GIS Cut Line= 3
     1668326.204      745083.397     1668320.996      745117.251
     1668331.413       745635.48
#Sta/Elev= 30
       0  959.06     8.6   957.3    17.1  955.14    25.7  952.18    53.8  939.63
    63.6  935.93    73.4  933.59    83.2  932.63    92.9  932.46   171.2   932.3
   200.5  931.78   220.1  931.06   239.6  930.06   249.4  930.11   256.6  931.15
   259.2  931.53   278.8  936.41   288.5   937.8   298.3  938.36   308.1  938.31
   347.2  936.23     357   936.3   396.1  938.41   464.6   938.5   484.1  939.11
   493.9  939.89   503.7  942.04   513.5  945.63   542.8  957.82   552.6  960.56
#Mann= 3 , 0 , 0
       0     .08       0   220.1    .045       0   256.6      .1       0
Bank Sta=220.1,256.6
XS Rating Curve= 0 ,0
Exp/Cntr=0.3,0.1

Type RM Length L Ch R = 1 ,3634.1  ,208.8,217.2,225.5
XS GIS Cut Line= 4
     1668224.642      745062.563      1668192.09      745171.938
     1668115.267      745500.063     1668093.131      745716.209
#Sta/Elev= 30
       0  950.34     9.5  946.97    28.5  939.26      38   936.3    47.6   934.9
    57.1  934.54    85.6  934.29   104.6  933.82   152.6  931.27   181.5   930.6
   191.1  930.04   210.4  928.31     220  927.42   229.7  927.08   239.3   927.5
   277.8  930.88   297.1  931.98   316.3  932.62   393.3  933.49   460.6  936.53
   498.4  937.83   507.8  938.88   517.2  941.56   536.1  948.91   545.6  951.25
     555  952.26   564.5   953.9   573.9  957.19   630.6  981.32   668.4  997.89
#Mann= 3 , 0 , 0
       0      .1       0   210.4    .045       0   239.3      .1       0
Bank Sta=210.4,239.3
XS Rating Curve= 0 ,0
Exp/Cntr=0.3,0.1

Type RM Length L Ch R = 1 ,3417    ,271.1,269.1,266.8
XS GIS Cut Line= 4
     1668093.131       745041.73     1668048.861      745074.282
     1667852.246      745362.043     1667801.465      745484.438
#Sta/Elev= 30
       0  949.88     9.2  943.83    18.3  937.29    27.5  932.86    36.6  931.86
    64.6  931.94    74.3   931.8    93.7  931.04   122.7  929.24   171.1  925.44
   180.8  924.83   190.5  924.71   200.2   925.3   229.2  927.76   248.6  928.97
   267.9  929.81   306.7  930.71   345.4  931.93   403.5  932.14   412.9  932.53
   422.4  933.23   431.9  934.47   441.3  936.48   460.3  942.17   469.7  944.49
   479.2  945.56   498.1  946.26   507.6  947.23     517  949.28     536  954.92
#Mann= 3 , 0 , 0
       0      .1       0   171.1    .045       0   200.2      .1       0
Bank Sta=171.1,200.2
XS Rating Curve= 0 ,0
Exp/Cntr=0.3,0.1

Type RM Length L Ch R = 1 ,3147.9  ,270.2,269.2,268.2
XS GIS Cut Line= 3
     1667801.852      744863.742     1667781.934      744984.438
     1667593.131      745311.261
#Sta/Elev= 30
       0  968.48    94.1  950.98   103.5  949.07   112.9  946.38   122.3  942.09
   141.7  929.88   151.4  925.04     161  922.55   170.7  921.65   180.4  921.42
   188.5  921.41   199.8  921.61   203.5  921.98   209.4  922.56   219.1   924.5
   228.8  926.67   238.5  928.98   267.5  936.65   277.2  939.08   286.8  940.62
   296.5  941.14   325.6  941.76   344.9  941.98   393.3  942.25   412.7  942.08
   441.7  941.14   451.4  940.91     461   940.8   490.1  940.83   499.8  940.76
#Mann= 3 , 0 , 0
       0      .1       0   180.4    .045       0   203.5      .1       0
Bank Sta=180.4,203.5
XS Rating Curve= 0 ,0
Exp/Cntr=0.3,0.1

Type RM Length L Ch R = 1 ,2878.6  ,437.2,427.1,417
XS GIS Cut Line= 3
     1667593.518      744792.128     1667544.954      744872.459
      1667354.85      745244.855
#Sta/Elev= 30
       0  967.89    37.6   960.4    56.3  955.86    65.7  953.21    75.1   950.4
    84.5  946.69    93.9  940.36   103.6  930.57   113.3  923.09     123  920.45
   132.8  920.06   142.5  920.09   149.2  920.34   152.2  920.45   181.4   922.4
   191.1  923.54   200.8  925.38   210.6  927.54   220.3  929.78     230  931.76
   239.7  932.73   249.4  932.61   259.2  932.62   307.8  933.39   317.5  933.48
   366.1  933.51   434.2  933.77   473.1  933.83   502.3   933.7     512  933.96
#Mann= 3 , 0 , 0
       0      .1       0     123    .045       0   149.2      .1       0
Bank Sta=123,149.2
XS Rating Curve= 0 ,0
Exp/Cntr=0.3,0.1

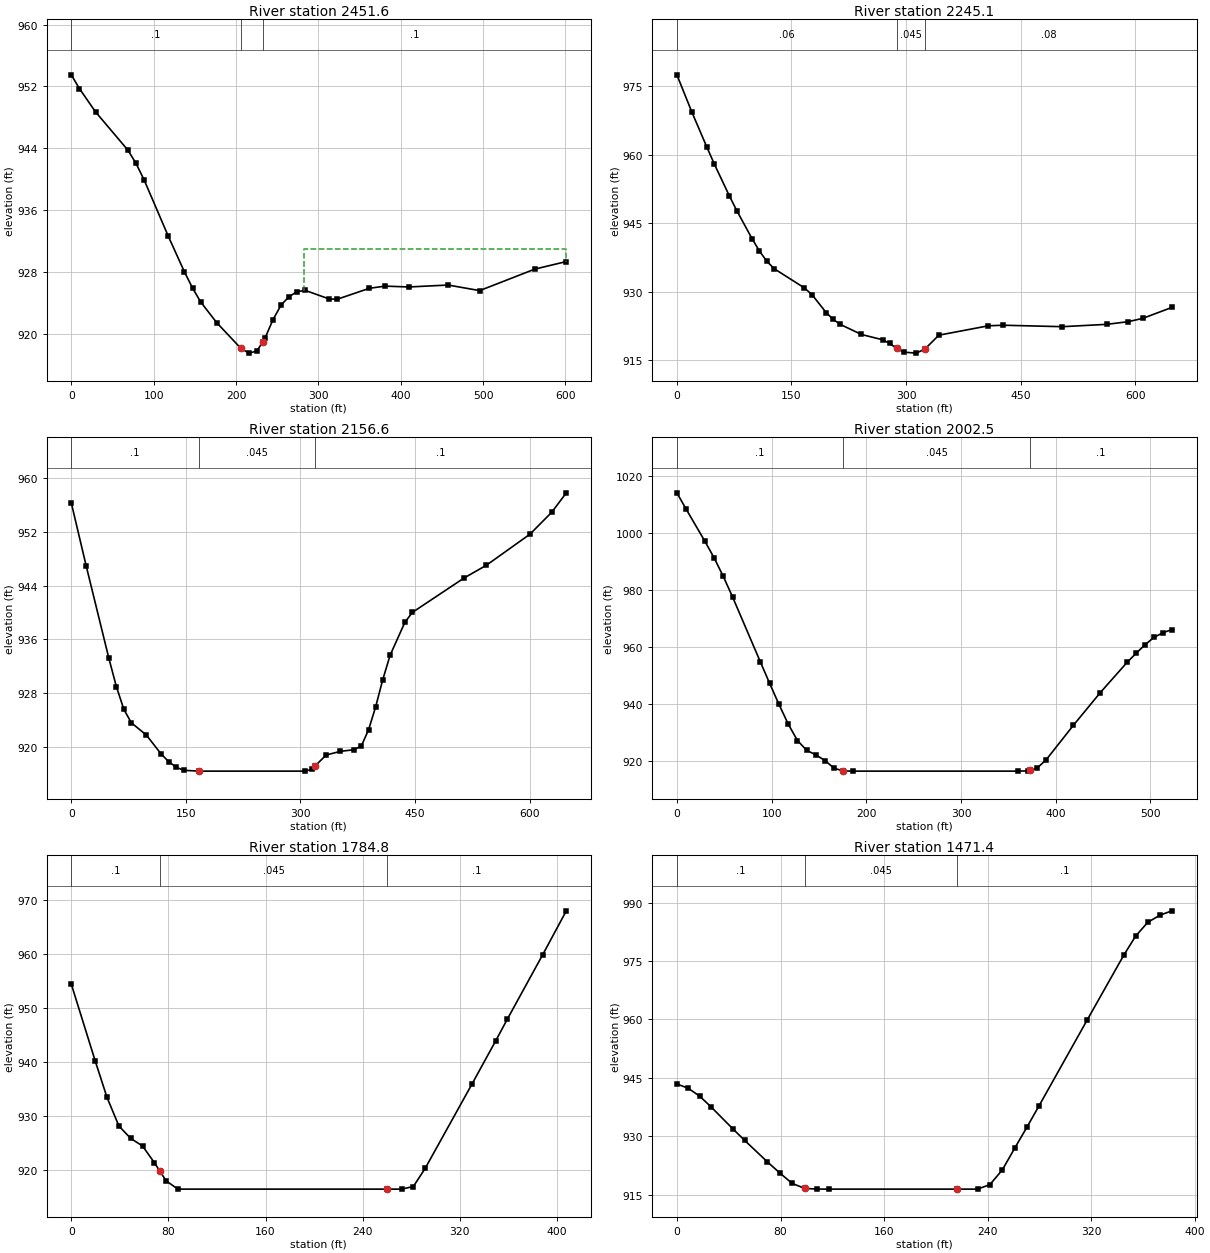
Type RM Length L Ch R = 1 ,2451.6  ,231.2,206.5,186.1
XS GIS Cut Line= 4
     1667154.583      744564.516     1667121.777       744697.98
     1667115.267      744912.824     1667274.121       745104.23
#Sta/Elev= 30
       0  953.49     9.8  951.72    29.4   948.7    68.7  943.75    78.5  942.05
    88.4   939.9   117.8   932.6   137.4  927.99   147.2  925.91     157  924.12
   176.5  921.43   205.8  918.11   215.6  917.48   225.4  917.75   232.3  918.91
   235.1  919.38   244.9  921.81   254.7  923.69   264.4  924.79   274.2  925.43
     284   925.6   313.3  924.48   323.1  924.46     362  925.87   381.1  926.15
   409.8  926.04   457.6  926.29   495.9  925.57   562.8  928.35   601.1  929.33
#Mann= 3 , 0 , 0
       0      .1       0   205.8    .045       0   232.3      .1       0
#XS Ineff= 2 , 0
                          282.11          930.92
Permanent Ineff=
       F       F
Bank Sta=205.8,232.3
XS Rating Curve= 0 ,0
Exp/Cntr=0.3,0.1

Type RM Length L Ch R = 1 ,2245.1  ,89.5,88.5,83.7
XS GIS Cut Line= 6
     1666663.444      744789.126     1666839.225      744808.657
     1666891.309      744828.188     1666955.111      744864.647
     1667033.236      744929.751     1667186.881      745114.647
#Sta/Elev= 30
       0  977.53    19.6  969.38    39.3  961.68    49.1  957.97    68.8  950.99
    78.6  947.74    98.3  941.69   108.1  938.95   117.9  936.68   127.7  935.05
     167  930.87   176.9   929.4   195.4  925.49   204.7  923.97     214  922.88
   241.7  920.68   269.2  919.53   278.4  918.75   287.6  917.64   296.8  916.82
   313.2   916.6   324.5  917.46     343  920.53   407.7  922.58   427.1  922.71
   504.7  922.39   562.6   922.9   591.1  923.49   610.1  924.22   648.1  926.61
#Mann= 3 , 0 , 0
       0     .06       0   287.6    .045       0   324.5     .08       0
Bank Sta=287.6,324.5
XS Rating Curve= 0 ,0
Exp/Cntr=0.3,0.1

Type RM Length L Ch R = 1 ,2156.6  ,153.5,154.1,154
XS GIS Cut Line= 6
     1666645.215      744875.063     1666820.996      744894.595
     1666873.079      744914.126     1666936.881      744950.584
     1667015.006      745015.688     1667168.652      745200.584
#Sta/Elev= 30
       0  956.34    19.6  946.91    49.1  933.24      59  928.99    68.8   925.6
    78.6   923.6    98.3  921.77   117.9  918.91   127.7   917.8   137.6  916.96
   147.4  916.52     167   916.4     306   916.4   315.2  916.67     319 917.148
   333.7   918.8   352.2  919.34   370.7   919.6   379.9  920.19   389.2  922.56
   398.4  925.94   407.7  929.99   417.4  933.66   436.8  938.57   446.5  940.03
   514.4  945.17   543.5  947.06   600.6  951.69   629.1  954.96   648.1  957.84
#Mann= 3 , 0 , 0
       0      .1       0     167    .045       0     319      .1       0
Bank Sta=167,319
XS Rating Curve= 0 ,0
Exp/Cntr=0.3,0.1

Type RM Length L Ch R = 1 ,2002.5  ,228.5,217.7,206.8
XS GIS Cut Line= 4
     1666517.828      744934.525     1666642.611      744959.699
     1666891.309      745092.511     1666987.663      745152.407
#Sta/Elev= 30
       0 1014.01     9.8 1008.27    29.4  997.12    39.2  991.28      49  984.69
    58.8  977.49    88.1  954.74    97.9  947.21   107.7  939.88   117.5  932.94
   127.3  927.14     137  923.71   146.7  922.12   156.5  920.08   166.2  917.37
   175.9  916.48   185.6   916.4   360.6   916.4   370.4   916.5     373916.7413
   380.1   917.4   389.8  920.33   418.7  932.49     447  943.91   475.4  954.56
   484.9  957.74   494.3  960.72   503.8   963.3   513.2  964.95   522.7  966.04
#Mann= 3 , 0 , 0
       0      .1       0   175.9    .045       0     373      .1       0
Bank Sta=175.9,373
XS Rating Curve= 0 ,0
Exp/Cntr=0.3,0.1

Type RM Length L Ch R = 1 ,1784.8  ,301.2,313.4,325.4
XS GIS Cut Line= 3
     1666572.298      745261.782     1666630.892      745257.876
      1666979.85      745261.782
#Sta/Elev= 19
       0  954.45    19.6  940.26    29.4  933.43    39.2  928.12    48.9  925.82
    58.7   924.4    68.4  921.32      73919.7171    78.1  917.94    87.8   916.4
     260   916.4     272   916.4   281.7  916.88   291.4  920.23   330.2  935.98
   349.5  943.91   359.2  947.98   388.3  959.93   407.7  968.05
#Mann= 3 , 0 , 0
       0      .1       0      73    .045       0     260      .1       0
Bank Sta=73,260
XS Rating Curve= 0 ,0
Exp/Cntr=0.3,0.1

Type RM Length L Ch R = 1 ,1471.4  ,399.1,407.6,415.9
XS GIS Cut Line= 4
     1666568.392      745493.553     1666632.194      745522.199
     1666804.069      745625.063     1666913.444      745648.501
#Sta/Elev= 25
       0   943.4     8.7  942.32    17.5   940.3    26.2  937.58    43.7  931.72
    52.4  928.89    69.9  923.39    79.5  920.53      89  917.87    98.6  916.59
   108.1  916.41   117.6   916.4     216   916.4   232.1   916.4   241.6  917.56
   251.2  921.34   260.7  926.89   270.2  932.31   279.6  937.84   316.8   959.9
   344.8  976.41   354.1  981.39   363.5  984.94   372.8  986.75   382.1  987.88
#Mann= 3 , 0 , 0
       0      .1       0    98.6    .045       0     216      .1       0
Bank Sta=98.6,216
XS Rating Curve= 0 ,0
Exp/Cntr=0.3,0.1

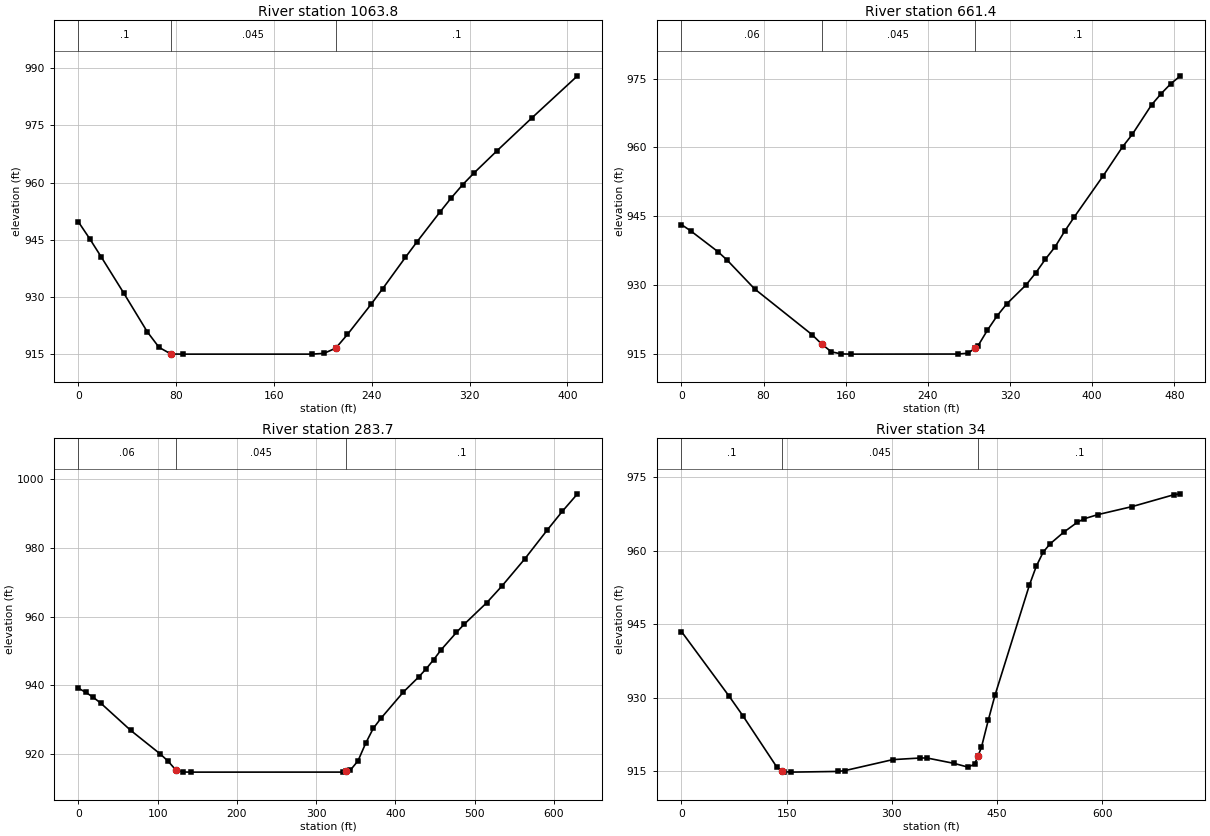
Type RM Length L Ch R = 1 ,1063.8  ,400.1,402.5,404.4
XS GIS Cut Line= 4
     1666331.413      745737.043     1666360.059       745760.48
     1666483.756      745920.636     1666561.881      746070.376
#Sta/Elev= 23
       0  949.62     9.2  945.22    18.5   940.5      37  930.96    56.3  920.76
    65.9  916.68    75.6  914.94    85.2   914.9   191.2   914.9   200.8   915.1
   210.5  916.47   220.1  920.08   239.4     928   248.8  932.06   267.5  940.34
   276.9  944.39   295.7  952.22   305.1     956   314.4  959.46   323.8  962.57
   342.6   968.4   370.7  976.91   408.3  988.05
#Mann= 3 , 0 , 0
       0      .1       0    75.6    .045       0   210.5      .1       0
Bank Sta=75.6,210.5
XS Rating Curve= 0 ,0
Exp/Cntr=0.3,0.1

Type RM Length L Ch R = 1 ,661.4   ,358.4,377.7,396.5
XS GIS Cut Line= 4
     1666084.017       745954.49     1666093.131      746043.032
     1666211.621      746226.626     1666281.934      746390.688
#Sta/Elev= 30
       0  943.16     8.9  941.81    35.6  937.24    44.5  935.41    71.2  929.14
     127  919.18   136.5  917.12     146   915.4   155.5  914.95     165   914.9
   269.5  914.92     279   915.1     286916.1979   288.5  916.59     298  920.13
   307.5  923.27   316.9  925.88   335.7  930.02   345.1  932.64   354.5  935.63
   363.9  938.31   373.3  941.74   382.7  944.86   410.9  953.86   429.6  960.13
     439  962.82   457.8  969.27   467.2  971.73   476.6   973.9     486  975.62
#Mann= 3 , 0 , 0
       0     .06       0   136.5    .045       0     286      .1       0
Bank Sta=136.5,286
XS Rating Curve= 0 ,0
Exp/Cntr=0.3,0.1

Type RM Length L Ch R = 1 ,283.7   ,234.1,249.7,265.2
XS GIS Cut Line= 4
     1665897.168      745995.723     1665840.744      746082.529
      1665766.96      746340.775      1665927.55      746542.598
#Sta/Elev= 30
       0  939.19     9.4  937.97    18.8  936.52    28.2  934.84    65.9  926.94
   103.5  920.03   113.1  917.98   122.7  915.48   132.3  914.84   141.9   914.8
   333.7  914.81     338915.0698   343.3  915.39   352.9  918.09   362.5  923.15
   372.1   927.5   381.7  930.41   410.3  938.12   429.4  942.44     439  944.85
   448.5  947.53   458.1  950.45   477.2  955.42   486.7  957.74   515.4  964.06
   534.5  968.88   563.2  976.73   591.8  985.19   610.9  990.65     630  995.72
#Mann= 3 , 0 , 0
       0     .06       0   122.7    .045       0     338      .1       0
Bank Sta=122.7,338
XS Rating Curve= 0 ,0
Exp/Cntr=0.3,0.1

Type RM Length L Ch R = 1 ,34      ,33.1,34,34.9
XS GIS Cut Line= 4
     1665783.401      745941.221     1665720.901      746028.026
     1665446.595      746229.415     1665189.651      746291.915
#Sta/Elev= 30
       0  943.49    68.1  930.27    87.5  926.32   136.1  915.81     144915.0765
   145.9   914.9   155.6   914.8   223.6  914.94   233.4  915.12   301.4  917.35
   340.3  917.68     350  917.69   388.9  916.58   408.4  915.83   418.1   916.4
     423918.1378   427.8  919.84   437.5  925.35   447.3  930.55   496.2  952.95
     506  956.78   515.8  959.67   525.6  961.36   545.2  963.76   564.8   965.8
   574.6  966.51   594.2  967.36   643.1     969   701.9  971.39   711.7  971.59
#Mann= 3 , 0 , 0
       0      .1       0     144    .045       0     423      .1       0
Bank Sta=144,423
XS Rating Curve= 0 ,0
Exp/Cntr=0.3,0.1

Chan Stop Cuts=-1
Use User Specified Reach Order=0
Composite Channel Slope=5